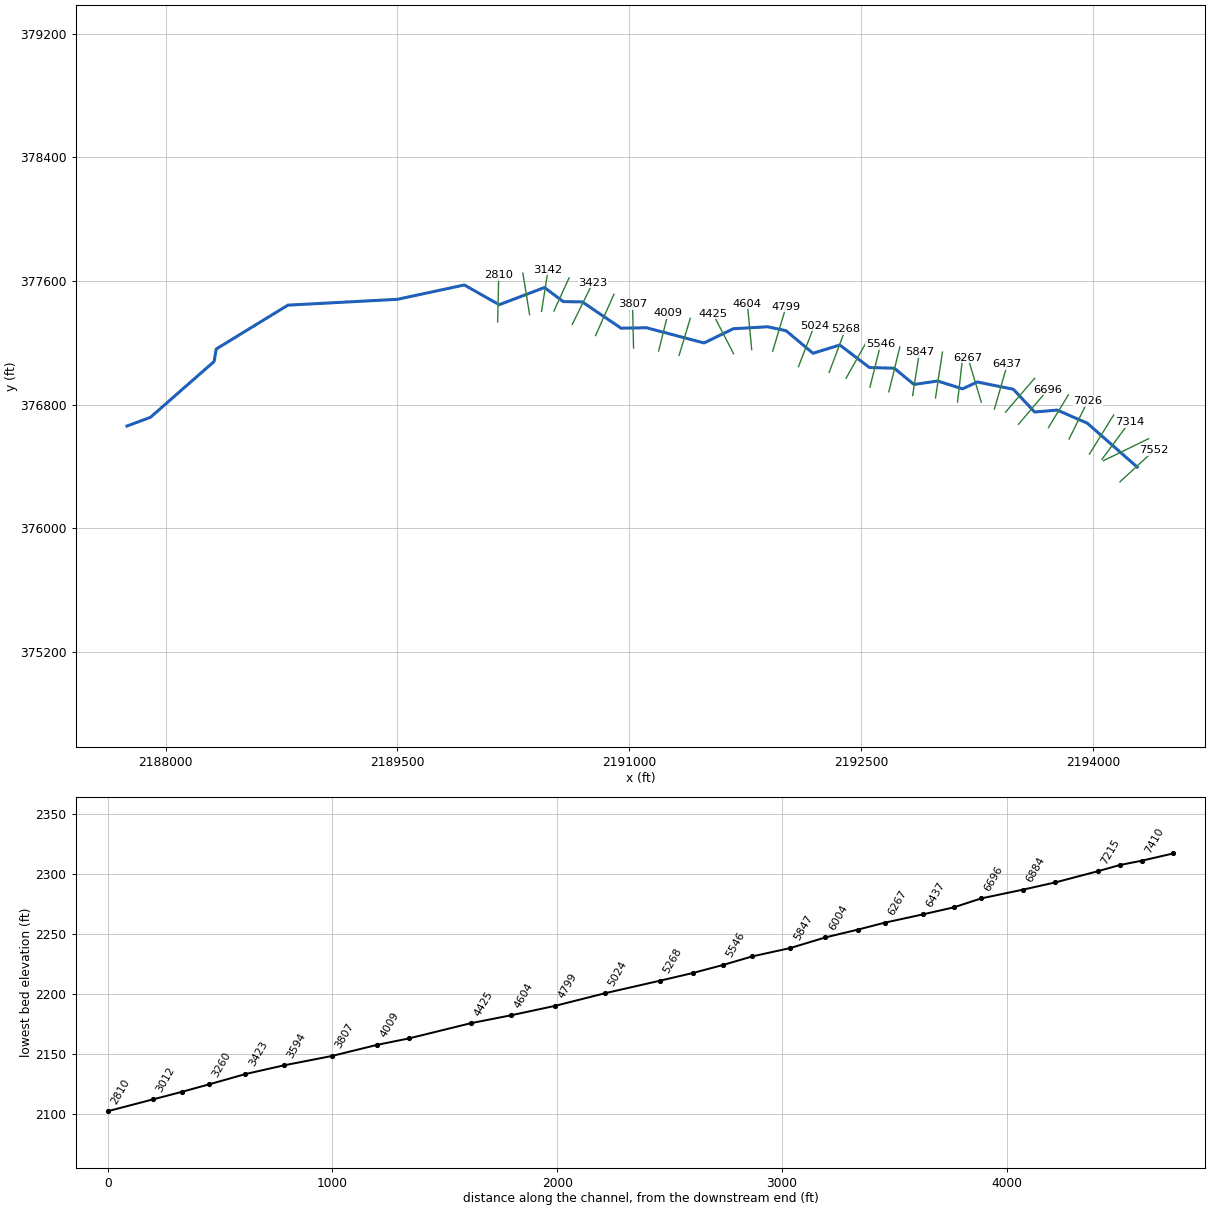
--- DAVYRN.prj (project) ---

Proj Title=DAVYRN
Current Plan=p01
Default Exp/Contr=0.3,0.1
English Units
Geom File=g01
Flow File=f01
Plan File=p01
Y Axis Title=Elevation
X Axis Title(PF)=Main Channel Distance
X Axis Title(XS)=Station
BEGIN DESCRIPTION:
Stream Name- Davy Run
Flood Zone: Zone A
Greenbrier County, WV
County-Wide Study
WVDHSEM-2018-3, Flood Risk Project
HEC-RAS Version: 5.0.7
General Notes:
For the Hydrology Regression was used.
END DESCRIPTION:
DSS Export Rating Curves= 0
DSS Export Rating Curve Sorted= 0
DSS Export Volume Flow Curves= 0
DXF Filename=DavyRun.
DXF OffsetX= 0
DXF OffsetY= 0
DXF ScaleX= 1
DXF ScaleY= 10

--- DAVYRN.p01 (plan) ---

Plan Title=Floodplain
Program Version=5.07
Short Identifier=Floodplain
Geom File=g01
Flow File=f01
Subcritical Flow
K Sum by GR= 0
Std Step Tol= 0.01
Critical Tol= 0.01
Num of Std Step Trials= 20
Max Error Tol= 0.3
Flow Tol Ratio= 0.001
Split Flow NTrial= 30
Split Flow Tol= 0.02
Split Flow Ratio= 0.02
Log Output Level= 0
Friction Slope Method= 1
Unsteady Friction Slope Method= 2
Unsteady Bridges Friction Slope Method= 1
Parabolic Critical Depth
Global Vel Dist= 0 , 0 , 0
Global Log Level= 0
CheckData=True
Encroach Param=-1 ,0,0, 0
Computation Interval=1MIN
Output Interval=1HOUR
Instantaneous Interval=1HOUR
Mapping Interval=1HOUR
Computation Time Step Use Courant=        0
Computation Time Step Use Time Series=    0
Computation Time Step Count To Double=0
Computation Time Step Max Doubling=0
Computation Time Step Max Halving=0
Computation Time Step Residence Courant=0
Run HTab= 0
Run UNet= 0
Run Sediment= 0
Run PostProcess= 0
Run WQNet= 0
Run RASMapper= 0
UNET Theta= 1
UNET Theta Warmup= 1
UNET ZTol= 0.02
UNET ZSATol= 0.02
UNET MxIter= 20
UNET Max Iter WO Improvement= 0
UNET MaxInSteps= 0
UNET DtIC= 0
UNET DtMin= 0
UNET MaxCRTS= 20
UNET WFStab= 2
UNET SFStab= 1
UNET WFX= 1
UNET SFX= 1
UNET 1D Methodology=Finite Difference
UNET DSS MLevel= 4
UNET Pardiso=0
UNET DZMax Abort= 100
UNET Use Existing IB Tables=-1
UNET Froude Reduction=False
UNET Froude Limit= 0.8
UNET Froude Power= 4
UNET D1 Cores= 0
UNET D2 Coriolis=0
UNET D2 Cores= 0
UNET D2 Theta= 1
UNET D2 Theta Warmup= 1
UNET D2 Z Tol= 0.01
UNET D2 Volume Tol= 0.01
UNET D2 Max Iterations= 20
UNET D2 Equation= 0
UNET D2 RampUpFraction=0.1
UNET D2 TimeSlices= 1
UNET D2 BCVolumeCheck=0
UNET D1D2 MaxIter= 0
UNET D1D2 ZTol=0.01
UNET D1D2 QTol=0.1
UNET D1D2 MinQTol=1
Write IC File= 0
Write IC File at Fixed DateTime=0
Write IC File at Sim End=0
Echo Input=False
Echo Parameters=False
Echo Output=False
Write Detailed= 0
HDF Write Warmup=0
HDF Write Time Slices=0
HDF Flush=0
HDF Face Node Velocities=0
HDF Compression= 1
HDF Chunk Size= 1
HDF Spatial Parts= 1
HDF Use Max Rows=0
HDF Fixed Rows= 1
Calibration Method= 0
Calibration Iterations= 20
Calibration Max Change=0.05
Calibration Tolerance=0.2
Calibration Maximum=1.5
Calibration Minimum=0.5
Calibration Optimization Method= 1
WQ AD Non Conservative
WQ ULTIMATE=-1
WQ Max Comp Step=1HOUR
WQ Output Interval=15MIN
WQ Output Selected Increments= 0
WQ Output face flow=0
WQ Output face velocity=0
WQ Output face area=0
WQ Output face dispersion=0
WQ Output cell volume=0
WQ Output cell surface area=0
WQ Output cell continuity=0
WQ Output cumulative cell continuity=0
WQ Output face conc=0
WQ Output face dconc_dx=0
WQ Output face courant=0
WQ Output face peclet=0
WQ Output face adv mass=0
WQ Output face disp mass=0
WQ Output cell mass=0
WQ Output cell source sink temp=0
WQ Output nsm pathways=0
WQ Output nsm derived pathways=0
WQ Output MaxMinRange=-1
WQ Daily Max Min Mean=-1
WQ Daily Range=0
WQ Daily Time=0
WQ Create Restart=0
WQ Fixed Restart=0
WQ System Summary=0
WQ Write To DSS=0
WQ Use Fixed Temperature=0
Sorting and Armoring Iterations= 10
XS Update Threshold= 0.02
Bed Roughness Predictor= 0
Hydraulics Update Threshold= 0.02
Energy Slope Method= 1
Volume Change Method= 1
Sediment Retention Method= 0
XS Weighting Method= 0
Number of US Weighted Cross Sections= 1
Number of DS Weighted Cross Sections= 1
Upstream XS Weight=0
Main XS Weight=1
Downstream XS Weight=0
Number of DS XS's Weighted with US Boundary= 1
Upstream Boundary Weight= 1
Weight of XSs Associated with US Boundary= 0
Number of US XS's Weighted with DS Boundary= 1
Downstream Boundary Weight= 0.5
Weight of XSs Associated with DS Boundary= 0.5
Percentile Method= 0
Sediment Output Level= 3
Mass or Volume Output= 0
Output Increment Type= 1
Profile and TS Output Increment= 1
XS Output Flag= 0
XS Output Increment= 10
Write Gradation File= 0
Read Gradation Hotstart= 0
Write HDF5 File= 1
Write Binary Output= 1
Write DSS Sediment File= 0
SV Curve= 0
Specific Gage Flag= 0

--- DAVYRN.f01 (steady flow) ---

Flow Title=Davy Run
Program Version=5.07
Number of Profiles= 6
Profile Names=f1p,f10p,f4p,f2p,f02p,f1pplus
River Rch & RM=Davy Run,A2              ,7552
     510     268     358     431     714     755
River Rch & RM=Davy Run,A2              ,7215
     600     318     422     509     838     888
River Rch & RM=Davy Run,A2              ,4425
     673     358     475     571     938     996
Boundary for River Rch & Prof#=Davy Run,A2              , 1
Up Type= 0
Dn Type= 3
Dn Slope=0.034
Boundary for River Rch & Prof#=Davy Run,A2              , 2
Up Type= 0
Dn Type= 3
Dn Slope=0.034
Boundary for River Rch & Prof#=Davy Run,A2              , 3
Up Type= 0
Dn Type= 3
Dn Slope=0.034
Boundary for River Rch & Prof#=Davy Run,A2              , 4
Up Type= 0
Dn Type= 3
Dn Slope=0.034
Boundary for River Rch & Prof#=Davy Run,A2              , 5
Up Type= 0
Dn Type= 3
Dn Slope=0.034
Boundary for River Rch & Prof#=Davy Run,A2              , 6
Up Type= 0
Dn Type= 3
Dn Slope=0.034
DSS Import GetInterval= 0
DSS Import GetPeak= 0
DSS Import FillOption= 0

--- DAVYRN.g01 (geometry) ---

Geom Title=Davy Run
Program Version=5.07

River Reach=Davy Run        ,A2
Reach XY= 30
2194285.72748105376396.1117716432193962.99945197376680.200770393
2193768.44472297  376765.13170292193622.05019215376752.593784547
 2193484.1139268376899.8889793162193250.57928889376946.898399726
2193155.66346823376902.383068815 2192994.4338038 376953.17463389
2192841.46790239376930.8675918882192713.52130789377036.039953724
2192553.65450163377040.3562180552192361.68703781377186.093787476
2192188.14276548377132.6860858952192013.64639531 377278.67365481
2191894.69847047377304.0052970652191672.80029222377291.357028395
2191483.27442455377199.3526192312191110.39295247377297.840939313
2190946.37589206377294.917716816 2190695.5368268377465.028925151
 2190573.2358903377466.857005477 2190450.9762923377557.845012471
2190158.20620856377446.786507562 2189932.8887458377574.329559565
 2189499.2675658377481.7641278952188791.41563505377443.911841393
 2188327.8191213377160.3047970532188313.73155105377079.170444891
2187902.13755797 376718.388686152187750.53746746376661.923247889

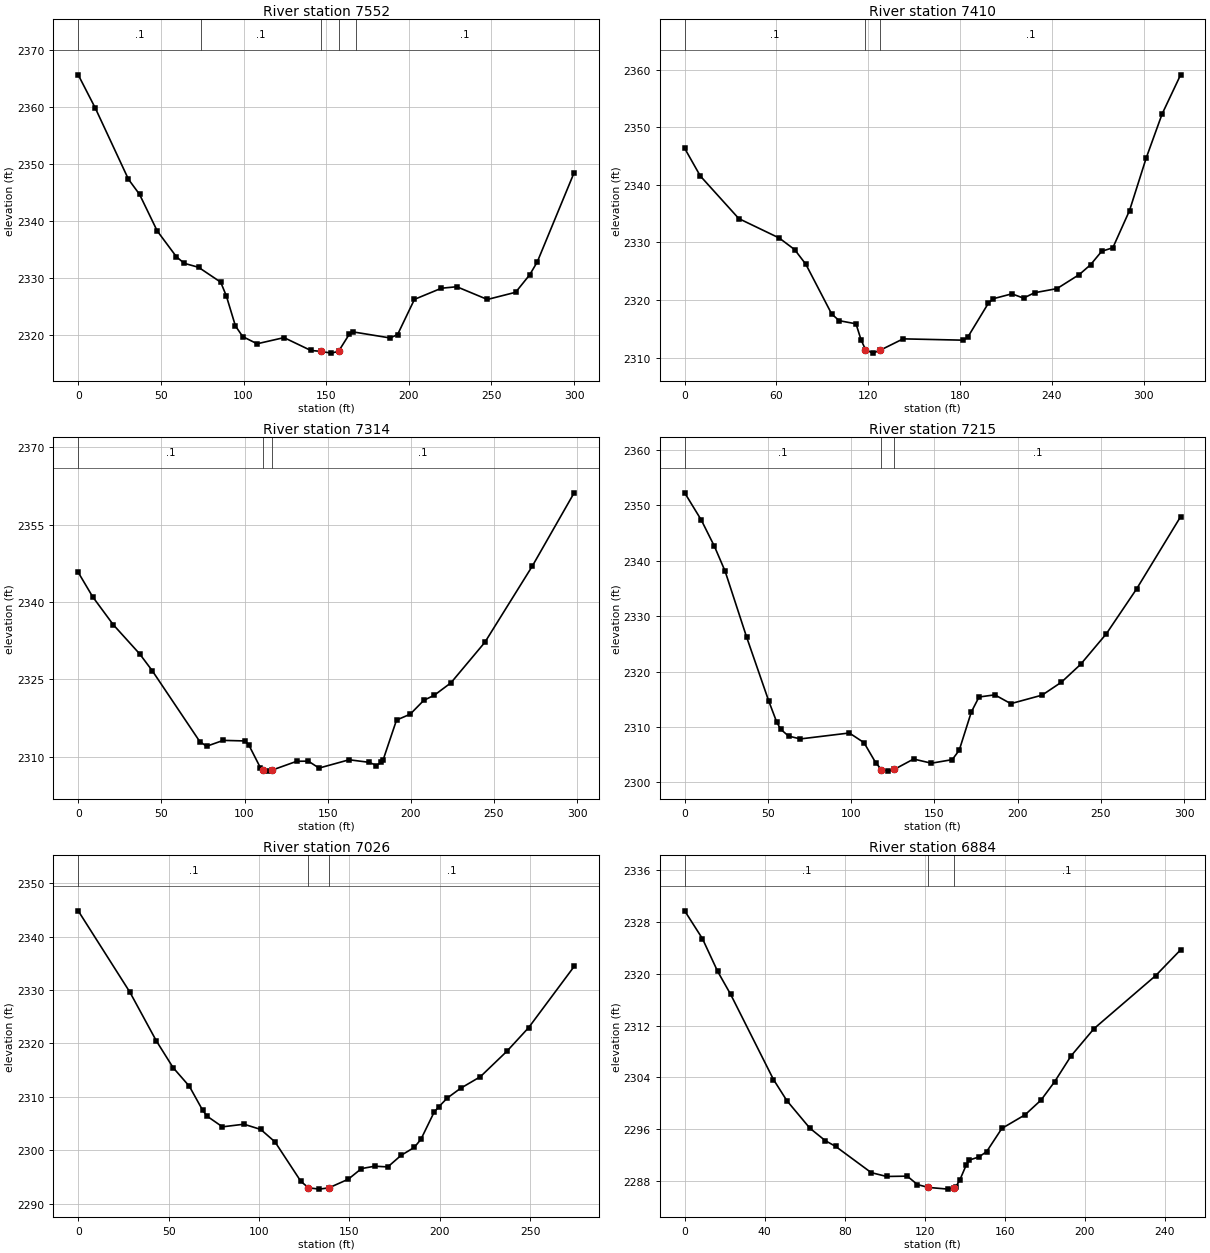
Type RM Length L Ch R = 1 ,7552    ,142.1,142.1,142.1
XS GIS Cut Line= 2
2194173.94389576 376300.854318692194394.64780238376504.053200573
#Sta/Elev= 30
       0 2365.67    10.4  2359.8    30.4 2347.35    37.1 2344.71    47.8 2338.29
    59.4 2333.77    64.1 2332.62    72.8 2331.92    86.2 2329.31    89.6  2326.9
    95.1 2321.64    99.5 2319.77   108.2 2318.51   124.5 2319.59   140.7 2317.34
   146.7 2317.18   153.1 2316.87   157.5 2317.19   163.9 2320.15   166.1  2320.6
   188.7 2319.53   193.2 2320.13   203.4  2326.3   219.7 2328.25     229 2328.51
   247.5 2326.28   264.6 2327.54   273.1  2330.6   277.7 2332.87     300 2348.53
#Mann= 5 ,-1 , 0
       0      .1       0   74.07      .1       0   146.7    .045       0
   157.5      .1       0  168.14      .1       0
Bank Sta=146.7,157.5
XS Rating Curve= 0 ,0
Exp/Cntr=0.3,0.1

Type RM Length L Ch R = 1 ,7410    ,95.6,95.6,95.6
XS GIS Cut Line= 2
2194067.71783758376438.034691536 2194359.2614978376579.919272834
#Sta/Elev= 30
       0 2346.34    10.2 2341.54    35.4 2334.13    61.8 2330.76    71.9 2328.74
    79.2  2326.2    96.1 2317.56     101  2316.4     112 2315.85   115.3 2313.07
   118.2 2311.37     123 2310.76     128 2311.29   142.8 2313.24     182 2313.01
     185 2313.51   198.5 2319.42   201.7 2320.21   213.9 2321.06   221.5 2320.32
   228.7 2321.25   243.4 2321.97     258 2324.42   265.3 2326.11   272.6 2328.45
   279.9 2329.07   290.8 2335.53   301.7 2344.66   312.1 2352.31   324.2 2359.11
#Mann= 3 ,-1 , 0
       0      .1       0   118.2    .045       0     128      .1       0
Bank Sta=118.2,128
XS Rating Curve= 0 ,0
Exp/Cntr=0.3,0.1

Type RM Length L Ch R = 1 ,7314    ,99.1,99.1,99.1
XS GIS Cut Line= 2
2194057.49275667 376446.45320815 2194234.8695361376686.170740139
#Sta/Elev= 30
       0 2345.77     8.7 2341.03      21 2335.65    36.9 2329.98    44.5 2326.71
    73.1 2312.97    77.2 2312.06    87.2  2313.2   100.2 2313.09   102.6  2312.3
   109.6 2307.86   111.3 2307.51   113.9 2307.24   116.6 2307.44   131.4 2309.15
   138.4 2309.17   144.8 2307.83   162.9 2309.44   175.1 2308.94   179.2 2308.33
   182.3 2308.95   183.3 2309.38   191.4 2317.14   199.6 2318.27   207.8 2320.96
   214.1 2321.95   224.1 2324.35   244.5  2332.2   273.1 2347.01   298.2 2361.18
#Mann= 3 ,-1 , 0
       0      .1       0   111.3    .045       0   116.6      .1       0
Bank Sta=111.3,116.6
XS Rating Curve= 0 ,0
Exp/Cntr=0.3,0.1

Type RM Length L Ch R = 1 ,7215    ,189,189,189
XS GIS Cut Line= 2
2193976.36749071376480.1465535742194133.18969798376733.436499574
#Sta/Elev= 30
       0 2352.24      10 2347.32    17.9 2342.57    24.3 2338.09    37.2 2326.22
    50.5 2314.68    55.2 2310.95    57.6 2309.61    62.4 2308.36    69.5 2307.85
    98.9 2308.92   107.7 2307.18   114.8 2303.53   118.2 2302.32     122 2302.04
   125.9 2302.35   137.5 2304.22   148.2 2303.47   160.7 2304.11   164.9  2305.8
   172.2 2312.72   176.8 2315.41   186.3  2315.8   195.9 2314.21   214.7 2315.75
   226.3 2318.08   237.8 2321.29   253.3 2326.82   271.4 2334.88   297.9 2347.94
#Mann= 3 ,-1 , 0
       0      .1       0   118.2    .045       0   125.9      .1       0
Bank Sta=118.2,125.9
XS Rating Curve= 0 ,0
Exp/Cntr=0.3,0.1

Type RM Length L Ch R = 1 ,7026    ,142.3,142.3,142.3
XS GIS Cut Line= 2
2193844.84890621 376577.975648452193966.36492467376824.052011129
#Sta/Elev= 30
       0 2344.83    28.6  2329.6    43.2  2320.5    52.5 2315.48    61.5 2311.99
    68.9 2307.47    71.4 2306.37    79.8  2304.4    91.7 2304.89     101 2303.91
   108.9 2301.57   123.2 2294.19   127.4 2292.99   133.4 2292.74   138.7 2292.98
   149.4 2294.59   156.7 2296.58     164 2297.03   171.3  2296.9   178.6 2299.05
   185.9 2300.54   189.6 2302.05   196.9 2307.13   199.5 2308.15   204.2 2309.79
   211.6 2311.62   222.5 2313.78   237.2 2318.55   249.2 2322.96   274.4 2334.42
#Mann= 3 ,-1 , 0
       0      .1       0   127.4    .045       0   138.7      .1       0
#XS Ineff= 2 , 0
                          164.05            2297
Permanent Ineff=
       F       F
Bank Sta=127.4,138.7
XS Rating Curve= 0 ,0
Exp/Cntr=0.3,0.1

Type RM Length L Ch R = 1 ,6884    ,188.1,188.1,188.1
XS GIS Cut Line= 2
2193711.38669731376651.833375703 2193840.3137826376863.688435466
#Sta/Elev= 30
       0 2329.68     8.9 2325.38    16.5 2320.34      23  2316.8    44.4 2303.69
    51.1 2300.43    62.6 2296.19    70.3 2294.27    75.5 2293.38    93.3 2289.34
     101 2288.75   111.3  2288.8   116.4  2287.5   121.9 2287.06   131.8  2286.8
   134.5 2286.99   135.6 2287.16   137.6 2288.22   140.8 2290.52   142.3 2291.28
   147.1 2291.75     151 2292.58   158.6 2296.15   170.2 2298.25   178.2 2300.52
     185 2303.35   193.2 2307.32   204.7 2311.53   235.5 2319.69     248 2323.67
#Mann= 3 ,-1 , 0
       0      .1       0   121.9    .045       0   134.5      .1       0
Bank Sta=121.9,134.5
XS Rating Curve= 0 ,0
Exp/Cntr=0.3,0.1

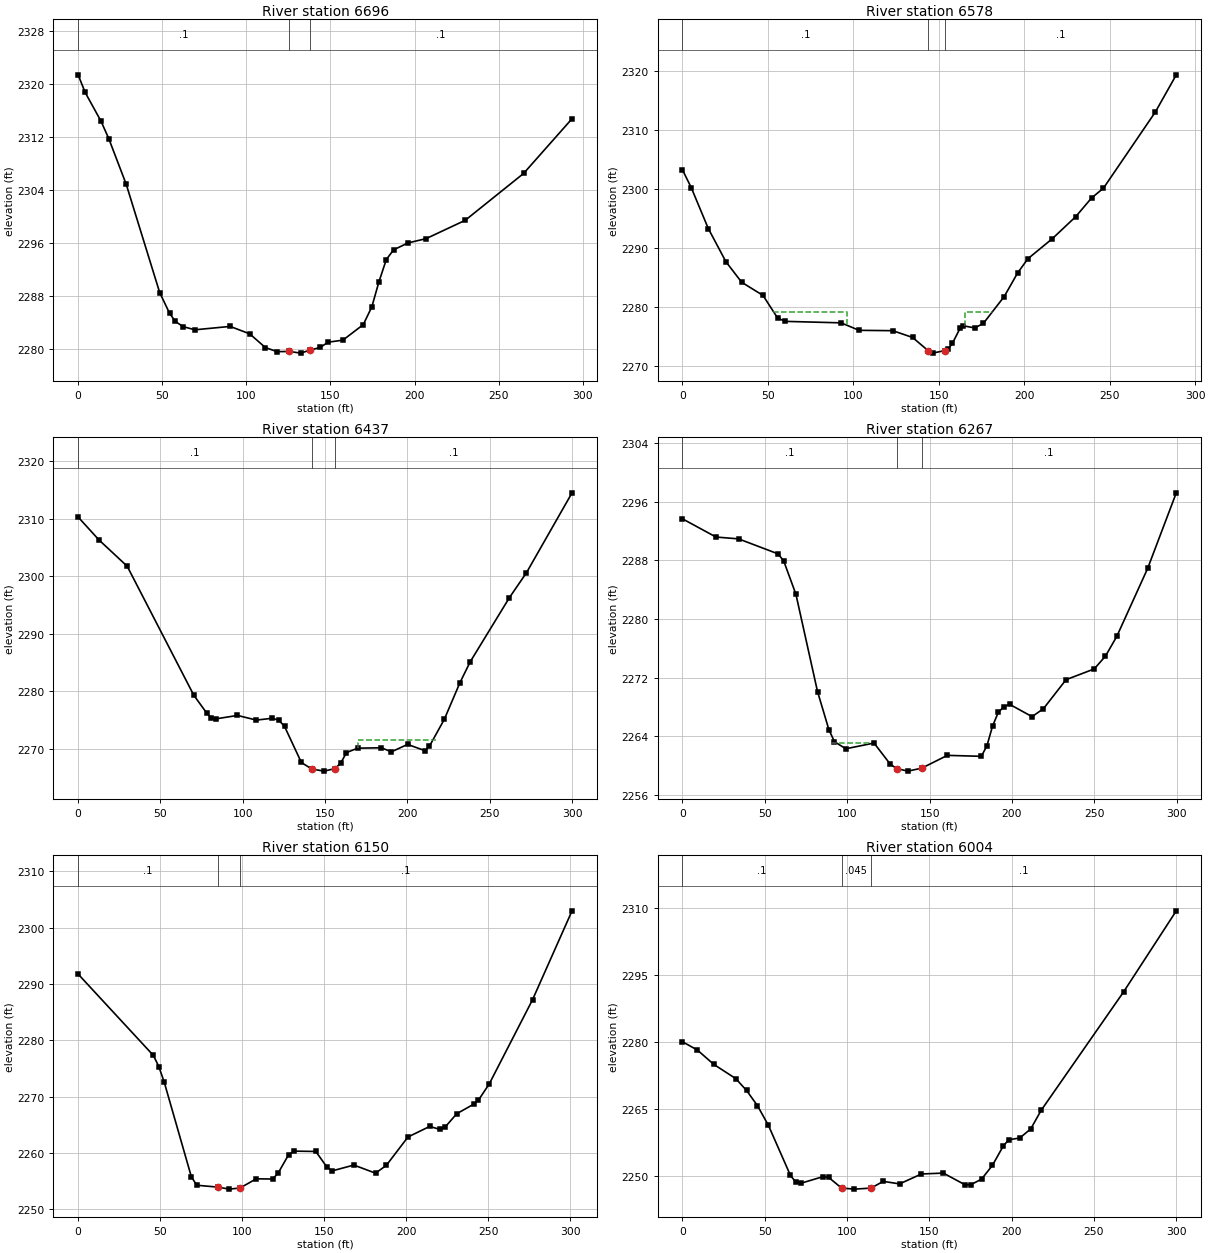
Type RM Length L Ch R = 1 ,6696    ,118.2,118.2,118.2
XS GIS Cut Line= 2
2193518.29245224376673.6484502192193707.72168483376897.911150322
#Sta/Elev= 30
       0 2321.41     4.2 2318.75    13.6 2314.42    18.2  2311.8    28.6 2304.89
    48.5 2288.55    54.4 2285.42    57.8  2284.2    62.4 2283.42    69.4 2282.94
    90.4 2283.45     102 2282.33   111.3 2280.26   118.3 2279.64   125.62279.673
   132.3 2279.42   138.1 2279.89   143.9 2280.28   148.6 2281.07   157.4 2281.38
   169.5 2283.72   174.6 2286.41   178.8 2290.17   183.2 2293.54   187.5    2295
   196.1 2296.05   206.8 2296.69   230.1 2299.46   264.8 2306.53   293.6 2314.79
#Mann= 3 , 0 , 0
       0      .1       0   125.6    .045       0   138.1      .1       0
Bank Sta=125.6,138.1
XS Rating Curve= 0 ,0
Exp/Cntr=0.3,0.1

Type RM Length L Ch R = 1 ,6578    ,141.2,141.2,141.2
XS GIS Cut Line= 2
 2193433.4484079376751.6060949862193621.97997484376970.587777541
#Sta/Elev= 30
       0  2303.3     5.2 2300.25    15.2 2293.29    25.5 2287.67    34.7 2284.19
    47.2 2281.95    55.8 2278.08    60.3 2277.55    92.9  2277.3   103.4 2276.03
   123.1 2275.97   134.7 2274.82     144 2272.53   146.4 2272.16   153.4 2272.58
   155.7 2272.93     158 2273.82   162.7  2276.5   164.1 2276.81   171.1 2276.44
   176.1  2277.2   188.3 2281.76   196.2 2285.79   202.2 2288.19   216.4 2291.57
   230.1 2295.31   239.4 2298.49   246.4 2300.17   276.7 2313.07     289  2319.4
#Mann= 3 ,-1 , 0
       0      .1       0     144    .045       0   153.4      .1       0
#XS Ineff= 2 ,-1
   52.96   96.12 2279.19  165.11  180.92 2279.06
Permanent Ineff=
       F       F
Bank Sta=144,153.4
XS Rating Curve= 0 ,0
Exp/Cntr=0.3,0.1

Type RM Length L Ch R = 1 ,6437    ,169.2,169.2,169.2
XS GIS Cut Line= 2
2193361.86407209376771.8858871042193445.27208035377060.057891568
#Sta/Elev= 30
       0 2310.26    12.7 2306.27    29.8 2301.72    70.3  2279.3    78.3 2276.15
    80.9 2275.36    83.6 2275.21    96.8 2275.81   108.3    2275     118 2275.32
     122 2274.96   125.4 2273.89   135.6 2267.64   141.9 2266.51   149.3 2266.14
   156.1 2266.58   159.6 2267.58     163 2269.36   169.8 2270.13   184.2 2270.19
   190.3 2269.49   200.1 2270.78   210.7 2269.69   213.4 2270.48   222.4 2275.12
   231.9 2281.49   238.1  2285.1     262 2296.28   272.3 2300.58     300 2314.46
#Mann= 3 ,-1 , 0
       0      .1       0   141.9    .045       0   156.1      .1       0
#XS Ineff= 1 ,-1
  170.28  217.09 2271.61
Permanent Ineff=
       F
Bank Sta=141.9,156.1
XS Rating Curve= 0 ,0
Exp/Cntr=0.3,0.1

Type RM Length L Ch R = 1 ,6267    ,117.4,117.4,117.4
XS GIS Cut Line= 2
2193276.66270618376817.0414498362193190.49535772377104.049986446
#Sta/Elev= 30
       0 2293.68    20.4 2291.19    34.1 2290.94    58.1 2288.89    61.5 2287.92
    68.9 2283.38      82 2270.12    88.9 2264.92    92.3 2263.27    99.2 2262.31
   116.3 2263.09   126.1 2260.22     130 2259.61   136.9 2259.26   145.3 2259.67
   160.8 2261.41   181.4 2261.28   184.8 2262.71   188.2  2265.4   191.7 2267.28
   195.1 2268.05   198.5 2268.38   212.2 2266.69   219.1 2267.78   232.8 2271.73
   249.9  2273.2   256.7 2274.94   263.6 2277.64   282.3  2286.9   299.7 2297.22
#Mann= 3 ,-1 , 0
       0      .1       0     130    .045       0   145.3      .1       0
#XS Ineff= 1 ,-1
   89.93  113.03 2263.14
Permanent Ineff=
       F
Bank Sta=130,145.3
XS Rating Curve= 0 ,0
Exp/Cntr=0.3,0.1

Type RM Length L Ch R = 1 ,6150    ,145.9,145.9,145.9
XS GIS Cut Line= 2
2193123.12572957376817.2449374222193157.45374289377116.359607643
#Sta/Elev= 30
       0 2291.75    45.9 2277.31    49.2 2275.34    52.5 2272.57      69 2255.82
    72.3 2254.29    85.5 2253.95    92.1  2253.6    98.7  2253.8   108.6 2255.43
   118.5 2255.39   121.8 2256.38   128.4 2259.74   131.7 2260.34   144.9 2260.28
   151.5 2257.58   154.8 2256.83   168.1 2257.87   181.3 2256.43   187.9 2257.82
   201.1 2262.85   214.3 2264.72   220.7 2264.19   223.7  2264.6   230.8 2266.97
   241.4 2268.71     244 2269.37   250.6 2272.25     277 2287.19   301.1 2302.97
#Mann= 3 ,-1 , 0
       0      .1       0    85.5    .045       0    98.7      .1       0
#XS Ineff= 2 ,-1
  148.94   168.7 2257.73  174.47  186.63 2256.99
Permanent Ineff=
       F       F
Bank Sta=85.5,98.7
XS Rating Curve= 0 ,0
Exp/Cntr=0.3,0.1

Type RM Length L Ch R = 1 ,6004    ,156.8,156.8,156.8
XS GIS Cut Line= 2
2192980.70523924376843.923232789 2193025.6018321377140.544701916
#Sta/Elev= 30
       0 2280.05     9.1 2278.19    19.1 2274.97    32.4  2271.8      39 2269.13
    45.6 2265.74    52.3  2261.3    65.6 2250.15    68.9  2248.6    72.2 2248.39
    85.5 2249.85    88.8 2249.69    96.7 2247.29   104.5 2247.05   114.6 2247.28
     122 2248.79   131.9 2248.22   145.2 2250.44   158.5 2250.64   171.7 2248.02
   175.1 2248.03   181.7 2249.28   188.3 2252.36     195 2256.76   198.3 2258.11
   204.9 2258.49   211.6 2260.53   217.9 2264.68     268 2291.21     300 2309.35
#Mann= 3 ,-1 , 0
       0      .1       0    96.7    .045       0   114.6      .1       0
#XS Ineff= 2 , 0
                          152.15         2250.41
Permanent Ineff=
       F       F
Bank Sta=96.7,114.6
XS Rating Curve= 0 ,0
Exp/Cntr=0.3,0.1

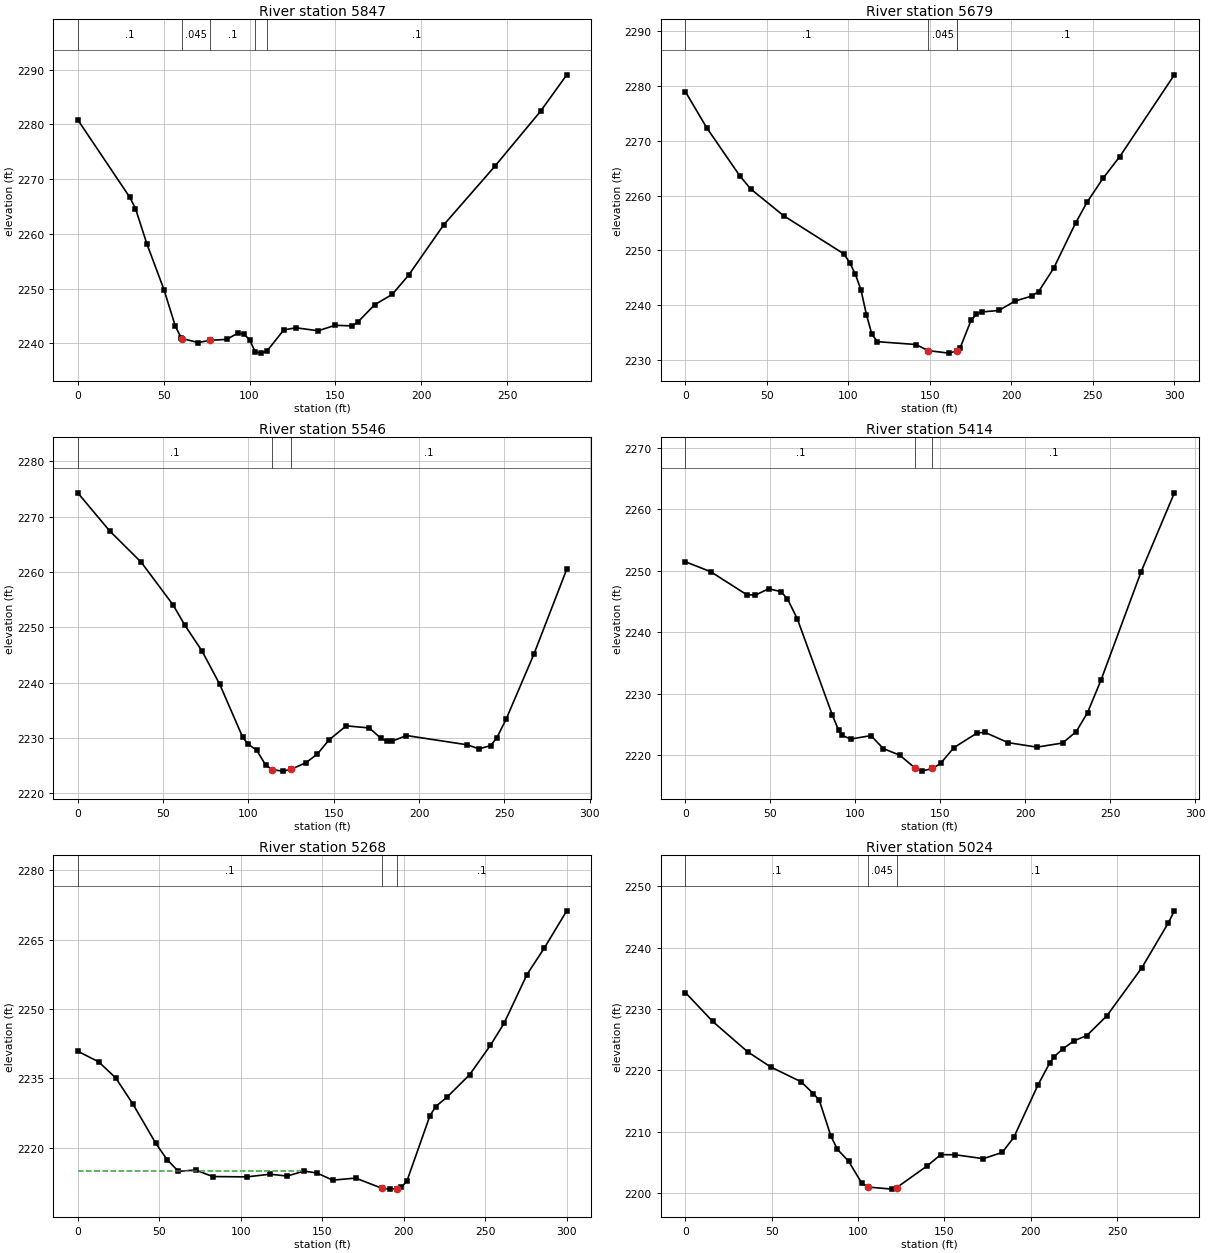
Type RM Length L Ch R = 1 ,5847    ,168.8,168.8,168.8
XS GIS Cut Line= 2
2192832.86846785376859.1533118652192876.92395428377140.330975276
#Sta/Elev= 30
       0 2280.86    30.3 2266.68    33.6 2264.62    40.2  2258.2    50.2 2249.78
    56.8 2243.11    60.2 2240.97    60.9 2240.84    70.1 2240.11    76.8 2240.52
    86.7 2240.69    93.4 2241.88    96.7 2241.64     100 2240.64   103.3 2238.41
   106.6 2238.18     110 2238.51   119.9 2242.42   126.9 2242.82   139.9 2242.27
   149.8 2243.27   159.8 2243.16   163.1 2243.89   172.8 2247.03     183 2248.91
   192.5 2252.41   212.9  2261.6   242.8 2272.37   269.4 2282.44   284.6 2289.08
#Mann= 5 ,-1 , 0
       0      .1       0    60.9    .045       0    76.8      .1       0
   103.3      .1       0     110      .1       0
#XS Ineff= 2 , 0
                           127.2         2242.78
Permanent Ineff=
       F       F
Bank Sta=60.9,76.8
XS Rating Curve= 0 ,0
Exp/Cntr=0.3,0.1

Type RM Length L Ch R = 1 ,5679    ,132.3,132.3,132.3
XS GIS Cut Line= 2
2192678.84107939376882.907218833 2192750.4105075377174.245196039
#Sta/Elev= 30
       0 2278.98    13.1 2272.38    33.4 2263.61    40.1 2261.21    60.4 2256.31
    97.4 2249.34   100.9 2247.72   104.3 2245.65   107.7 2242.82   111.1 2238.27
   114.4 2234.71   117.8 2233.35   141.5 2232.83   148.9 2231.72   161.7 2231.26
   166.72231.665   168.5 2232.16   175.3 2237.27   178.6 2238.36     182 2238.78
   192.3 2239.04   202.3 2240.77   212.4 2241.66   216.7 2242.49   225.9 2246.72
   239.4    2255   246.5 2258.83   256.3 2263.19   266.5 2267.12     300 2282.04
#Mann= 4 ,-1 , 0
       0      .1       0   148.9    .045       0   166.7      .1       0
  166.73      .1       0
Bank Sta=148.9,166.7
XS Rating Curve= 0 ,0
Exp/Cntr=0.3,0.1

Type RM Length L Ch R = 1 ,5546    ,132.6,132.6,132.6
XS GIS Cut Line= 2
2192556.87380284376913.5747951152192626.19640649377191.513084498
#Sta/Elev= 30
       0 2274.28    18.7  2267.4    37.2 2261.74    55.9 2254.02    62.6 2250.44
    72.8 2245.71    83.2 2239.69    96.7 2230.09    99.8 2228.89   104.8 2227.79
   110.2 2225.06   114.1 2224.26   120.1 2224.01   124.8 2224.32   133.7 2225.53
   140.4  2227.1   147.2 2229.64   157.3 2232.19   170.8 2231.81   177.6 2229.95
     181 2229.43   184.4 2229.45   192.6 2230.44   228.3 2228.76   235.1 2228.03
   241.9 2228.62   245.6 2230.07     251 2233.41   267.2 2245.09   286.5 2260.49
#Mann= 3 ,-1 , 0
       0      .1       0   114.1    .045       0   124.8      .1       0
#XS Ineff= 2 , 0
                          162.31         2231.91
Permanent Ineff=
       F       F
Bank Sta=114.1,124.8
XS Rating Curve= 0 ,0
Exp/Cntr=0.3,0.1

Type RM Length L Ch R = 1 ,5414    ,145.8,145.8,145.8
XS GIS Cut Line= 2
2192402.03172552376971.2356523412192543.26843203377221.963200139
#Sta/Elev= 30
       0 2251.46    14.9 2249.84    36.1 2246.11    41.2 2246.03      49 2247.07
    56.3  2246.6    60.1 2245.42    65.9 2242.17    86.4 2226.62    90.2 2224.05
    92.4 2223.24    97.2 2222.64   109.2  2223.2   116.6 2221.08   126.1 2220.03
   135.4 2217.89   139.1 2217.43   145.4 2217.86   150.2 2218.68     158 2221.24
   171.9 2223.66   176.5 2223.71   189.9 2222.06   206.9 2221.33     222    2222
     230 2223.84   236.7 2226.94   244.6 2232.21   268.2 2249.81   287.8 2262.66
#Mann= 3 ,-1 , 0
       0      .1       0   135.4    .045       0   145.4      .1       0
#XS Ineff= 2 , 0
                          173.25         2223.54
Permanent Ineff=
       F       F
Bank Sta=135.4,145.4
XS Rating Curve= 0 ,0
Exp/Cntr=0.3,0.1

Type RM Length L Ch R = 1 ,5268    ,243.8,243.8,243.8
XS GIS Cut Line= 2
 2192292.6996613377008.3460996912192398.14945377377289.202542152
#Sta/Elev= 30
       0 2240.87    12.8 2238.58    23.3  2235.1    33.8 2229.48    47.8    2221
    54.8 2217.43    61.8 2214.88    72.3 2215.19    82.8 2213.77   103.9  2213.7
   117.9 2214.28   128.4 2213.88   138.9 2214.95   146.8 2214.53   156.4 2212.99
   170.5 2213.44   186.9 2211.19   191.5 2211.05   195.9 2211.18   198.5 2211.43
     202 2212.86     216 2226.86   219.5 2228.89   226.5 2230.92   240.4 2235.79
   253.2 2242.16   261.6 2246.95   275.6 2257.46   286.3 2263.22     300 2271.23
#Mann= 3 ,-1 , 0
       0      .1       0   186.9    .045       0   195.9      .1       0
#XS Ineff= 2 , 0
          138.75 2214.97
Permanent Ineff=
       F       F
Bank Sta=186.9,195.9
XS Rating Curve= 0 ,0
Exp/Cntr=0.3,0.1

Type RM Length L Ch R = 1 ,5024    ,224.9,224.9,224.9
XS GIS Cut Line= 2
2192094.29119529 377046.389129212192196.60855025377310.513505412
#Sta/Elev= 30
       0 2232.68    15.8 2227.98    36.1 2223.02    49.4 2220.56      67 2218.15
    74.2  2216.2    77.6  2215.1    84.3 2209.29    88.1 2207.12    94.5 2205.22
   102.2 2201.61   105.7    2201   119.7 2200.66   122.4 2200.91   140.1 2204.46
   147.9 2206.27   156.2 2206.26   172.6 2205.62   183.5 2206.64   190.2 2209.08
   204.2 2217.62   211.1 2221.25   213.6 2222.23   218.7 2223.54   225.3 2224.85
   232.4 2225.65   244.1 2228.89   264.4 2236.73   279.6 2243.98   283.2 2245.99
#Mann= 3 ,-1 , 0
       0      .1       0   105.7    .045       0   122.4      .1       0
Bank Sta=105.7,122.4
XS Rating Curve= 0 ,0
Exp/Cntr=0.3,0.1

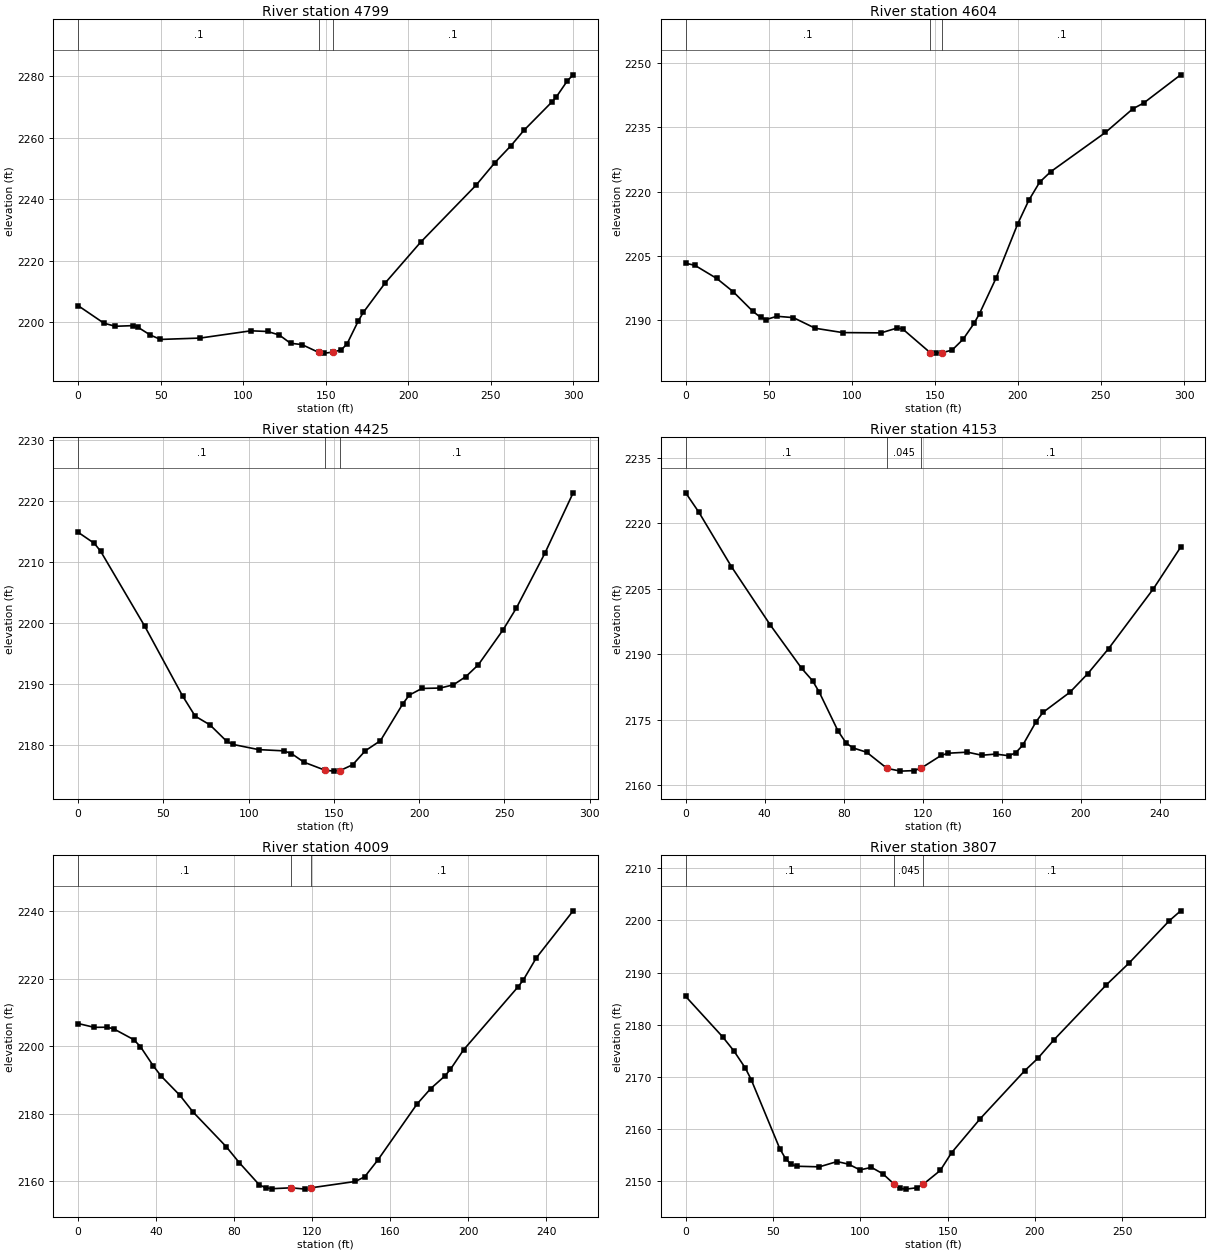
Type RM Length L Ch R = 1 ,4799    ,194.8,194.8,194.8
XS GIS Cut Line= 2
2191927.47168819377146.3973996542192014.01179673377433.644348484
#Sta/Elev= 30
       0 2205.46    15.6 2199.78    22.5 2198.77    33.2 2198.98    36.2 2198.47
    43.7 2195.93    49.9  2194.5    73.9 2194.94   104.7  2197.3   114.8 2197.08
   121.9 2195.94   128.7 2193.25   135.6 2192.83   145.8 2190.28   149.3 2190.05
   154.5 2190.36   159.6 2191.17     163 2193.09   169.8 2200.52   172.8 2203.26
   185.9 2212.72   207.5 2226.04   241.2 2244.62   252.6 2251.93   262.3 2257.42
   270.2 2262.43     287 2271.56   289.8 2273.26   296.5  2278.5     300 2280.44
#Mann= 3 ,-1 , 0
       0      .1       0   145.8    .045       0   154.5      .1       0
#XS Ineff= 2 , 0
          106.99 2197.13
Permanent Ineff=
       F       F
Bank Sta=145.8,154.5
XS Rating Curve= 0 ,0
Exp/Cntr=0.3,0.1

Type RM Length L Ch R = 1 ,4604    ,179.1,179.1,179.1
XS GIS Cut Line= 2
2191791.73366346377155.8799704922191763.59207438377452.516564958
#Sta/Elev= 30
       0 2203.26     5.5 2202.79    18.7 2199.71    28.6 2196.61    40.4 2192.04
    45.1 2190.61    48.4  2190.1    54.9 2190.87    64.8 2190.56      78 2188.07
    94.5 2187.06   117.6 2186.99   127.4 2188.14   130.7 2187.88   147.2 2182.37
   150.5 2182.26   154.3 2182.36   160.4 2182.97     167 2185.49   173.6 2189.21
   176.9  2191.5   186.8 2199.75   199.9 2212.47   206.5 2217.93   213.1 2222.21
   219.7 2224.64   252.7 2233.83   269.2 2239.36   275.7  2240.7     298  2247.3
#Mann= 3 ,-1 , 0
       0      .1       0   147.2    .045       0   154.3      .1       0
Bank Sta=147.2,154.3
XS Rating Curve= 0 ,0
Exp/Cntr=0.3,0.1

Type RM Length L Ch R = 1 ,4425    ,272.1,272.1,272.1
XS GIS Cut Line= 2
2191674.46832457377129.9649784622191541.00611567377387.819149069
#Sta/Elev= 30
       0 2214.88     9.5 2213.06    13.2 2211.76    39.1 2199.44    61.2 2188.04
    68.6 2184.71    77.3 2183.27    87.1 2180.58    90.8 2180.06   105.9 2179.21
   120.5 2179.01   125.1 2178.56   132.4 2177.15   144.6 2175.85   149.9 2175.68
   153.6 2175.77     161 2176.73   168.4 2179.02   177.3 2180.68   190.5 2186.77
   194.2 2188.16   201.6 2189.25   212.4 2189.32   220.1 2189.85   227.4  2191.2
   234.7 2193.14   249.3 2198.91     257 2202.45   273.7 2211.43   290.3 2221.36
#Mann= 3 ,-1 , 0
       0      .1       0   144.6    .045       0   153.6      .1       0
Bank Sta=144.6,153.6
XS Rating Curve= 0 ,0
Exp/Cntr=0.3,0.1

Type RM Length L Ch R = 1 ,4153    ,144,144,144
XS GIS Cut Line= 2
2191322.02443311377119.5989816522191394.58641076377359.312657835
#Sta/Elev= 30
       0    2227     6.7 2222.53    23.1  2210.1    42.9 2196.63    58.7 2186.73
    64.2  2183.9    67.6 2181.27    77.1 2172.36    81.3 2169.54    84.8 2168.47
    91.6 2167.49   101.9 2163.79   108.7 2163.16   115.6 2163.28   119.1 2163.83
   129.3 2166.77   132.8 2167.27   142.6 2167.51   149.9  2166.8   156.8 2167.07
   163.6 2166.69     167 2167.38   170.5 2169.05   177.3 2174.47   180.8 2176.63
   194.5 2181.27   203.5 2185.52     214 2191.25   236.7 2204.99   250.5 2214.54
#Mann= 3 ,-1 , 0
       0      .1       0   101.9    .045       0   119.1      .1       0
Bank Sta=101.9,119.1
XS Rating Curve= 0 ,0
Exp/Cntr=0.3,0.1

Type RM Length L Ch R = 1 ,4009    ,201.8,201.8,201.8
XS GIS Cut Line= 2
2191189.47700182377146.8575673212191251.40607985377393.002147457
#Sta/Elev= 30
       0 2206.78     8.2 2205.65      15 2205.68    18.3 2205.18    28.5    2202
    31.9 2199.95    38.6 2194.15    42.6 2191.17    52.2 2185.48    58.9 2180.56
    75.9 2170.29    82.6 2165.55    92.8 2159.02    96.2 2158.05    99.5 2157.83
   109.2 2158.09   116.5  2157.7   119.2 2158.07   142.1 2159.97   146.9 2161.34
   153.7 2166.36   173.7 2182.88   180.7 2187.46   188.1 2191.27   190.9 2193.22
   197.6 2198.96   225.5 2217.62   228.2 2219.63   234.9 2226.23   253.8 2240.18
#Mann= 3 ,-1 , 0
       0      .1       0   109.2    .045       0   119.2      .1       0
Bank Sta=109.2,119.2
XS Rating Curve= 0 ,0
Exp/Cntr=0.3,0.1

Type RM Length L Ch R = 1 ,3807    ,213.1,213.1,213.1
XS GIS Cut Line= 2
2191027.44196752377166.5621498282191020.76265088377450.015129906
#Sta/Elev= 30
       0 2185.41    21.1 2177.68    27.6 2174.96    34.2 2171.64    37.5 2169.46
    53.9 2156.19    57.2 2154.28    60.4 2153.18    63.7 2152.82    76.6 2152.71
    86.7 2153.72    93.3 2153.22    99.8 2152.12   106.4  2152.6   112.9 2151.38
   119.5 2149.35   122.8 2148.56   126.1 2148.43   132.6  2148.7   135.9 2149.32
   145.8 2152.01   152.3 2155.42   168.7 2161.95   194.2 2171.16   201.6  2173.5
     211 2177.11   240.9 2187.62   254.1 2191.87     277 2199.94   283.5 2201.84
#Mann= 3 ,-1 , 0
       0      .1       0   119.5    .045       0   135.9      .1       0
#XS Ineff= 2 , 0
           86.67  2153.7
Permanent Ineff=
       F       F
Bank Sta=119.5,135.9
XS Rating Curve= 0 ,0
Exp/Cntr=0.3,0.1

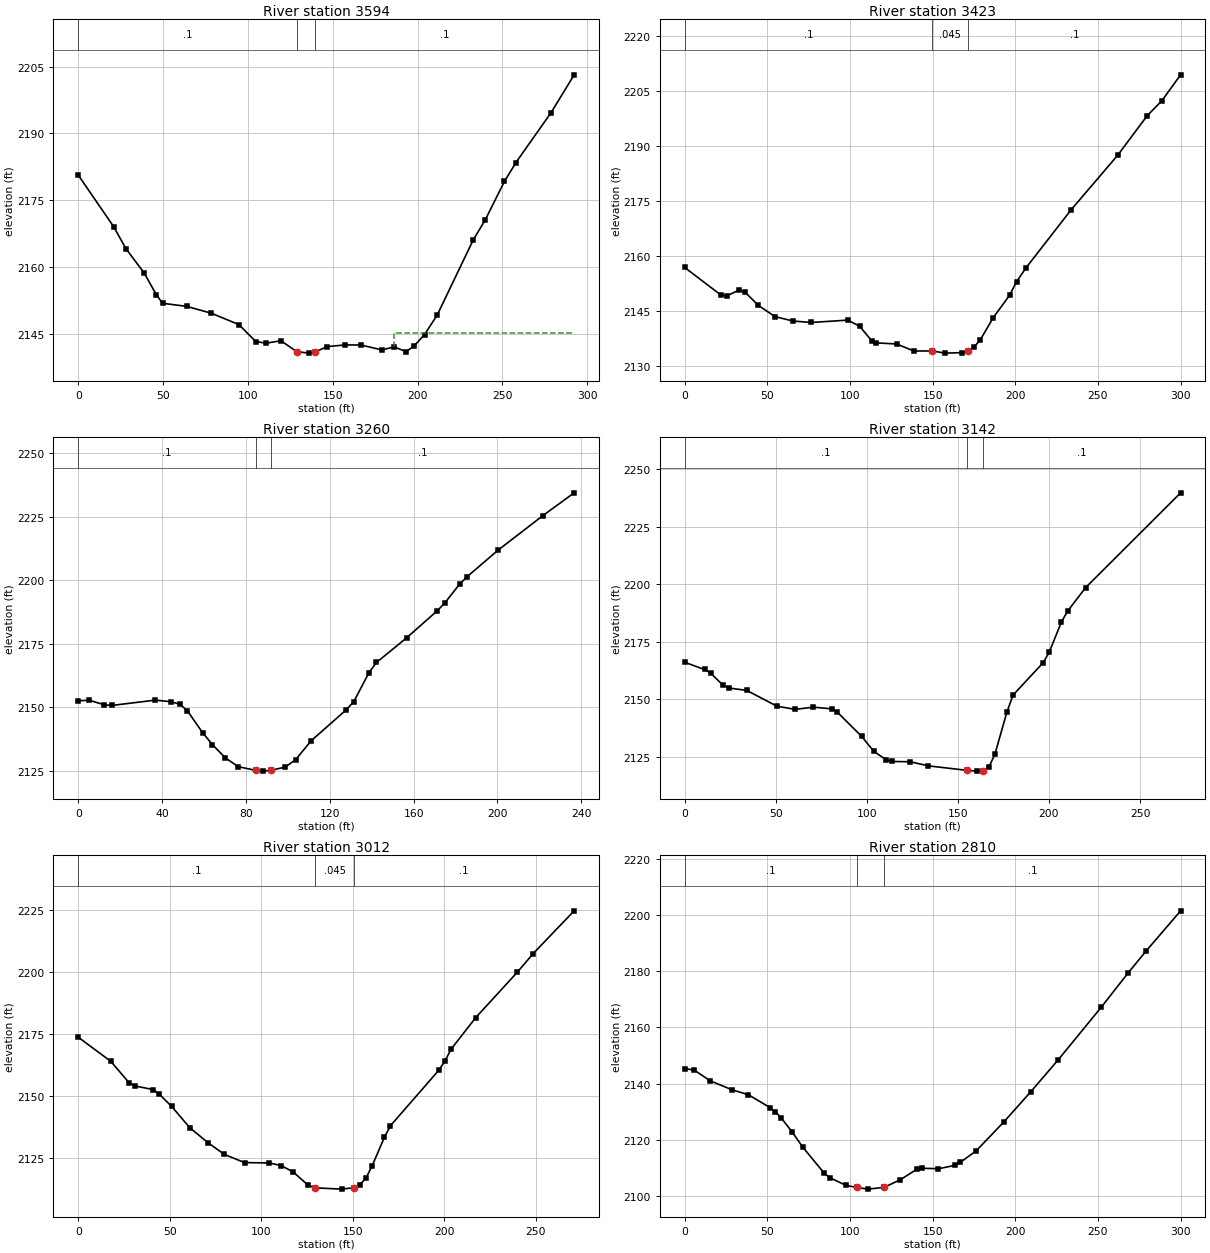
Type RM Length L Ch R = 1 ,3594    ,171,171,171
XS GIS Cut Line= 2
 2190781.6968495377247.2303173542190900.62980904377514.191051982
#Sta/Elev= 30
       0 2180.65    20.9 2169.05    28.1 2164.13    38.9 2158.64    46.1 2153.73
    49.7 2151.86      64 2151.15    78.4 2149.63    94.7 2147.07   104.6 2143.27
   110.7 2142.89   119.5 2143.44   128.7 2141.01   135.9 2140.66   139.5 2140.88
   146.6 2142.12   157.4  2142.5   166.7 2142.48     179 2141.38   186.2 2142.05
   193.3    2141   197.9 2142.24   204.1 2144.82   211.5 2149.15   232.8 2166.06
     240 2170.66   251.2  2179.2     258 2183.46   278.6 2194.61   292.3 2203.15
#Mann= 3 ,-1 , 0
       0      .1       0   128.7    .045       0   139.5      .1       0
#XS Ineff= 2 , 0
                          186.23         2145.14
Permanent Ineff=
       F       F
Bank Sta=128.7,139.5
XS Rating Curve= 0 ,0
Exp/Cntr=0.3,0.1

Type RM Length L Ch R = 1 ,3423    ,162.8,162.8,162.8
XS GIS Cut Line= 2
2190630.86728051377319.0892110712190763.29310252377588.279481451
#Sta/Elev= 30
       0 2156.82    21.7 2149.36    25.3 2149.01    32.6  2150.6    36.3 2150.16
    44.6 2146.45    54.6  2143.4    65.5 2142.19    76.5 2141.79    98.5 2142.43
   105.8 2140.79   113.1 2136.81   115.6 2136.22   128.2 2135.92   138.7 2133.99
   149.9 2134.02   157.3 2133.42   167.9 2133.55   171.6 2134.12   175.2 2135.17
   178.9  2137.1   186.7 2143.15   196.5 2149.19   200.8 2152.96   206.3 2156.61
   233.7 2172.54     262 2187.51   279.8 2198.28   288.6 2202.34     300 2209.44
#Mann= 3 ,-1 , 0
       0      .1       0   149.9    .045       0   171.6      .1       0
Bank Sta=149.9,171.6
XS Rating Curve= 0 ,0
Exp/Cntr=0.3,0.1

Type RM Length L Ch R = 1 ,3260    ,118.6,118.6,118.6
XS GIS Cut Line= 2
 2190512.1809325 377405.959643472190610.65790217377621.054077238
#Sta/Elev= 30
       0 2152.51     5.2  2152.7    12.4 2150.93      16 2150.65    36.8 2152.75
    44.2 2152.12    48.5 2151.16    52.1 2148.53    59.3 2139.99      64 2135.28
    70.2 2129.99    76.4 2126.55    84.6 2125.11    88.2  2124.8    91.8 2125.11
    98.7 2126.36   103.7 2129.28   111.1 2136.72   127.9 2148.97   131.5 2152.18
   138.7 2163.55   142.3 2167.57   156.8 2177.36   171.2 2187.86   174.8 2190.91
     182 2198.45   185.6 2201.39   200.4 2211.85   221.7 2225.39   236.6 2234.35
#Mann= 3 ,-1 , 0
       0      .1       0    84.6    .045       0    91.8      .1       0
Bank Sta=84.6,91.8
XS Rating Curve= 0 ,0
Exp/Cntr=0.3,0.1

Type RM Length L Ch R = 1 ,3142    ,130.2,130.2,130.2
XS GIS Cut Line= 2
2190432.02792142377403.2737762552190474.60419407377672.236186465
#Sta/Elev= 30
       0 2166.05    10.9 2162.91    14.2 2161.36    20.8 2156.27    24.1 2154.88
    34.1 2153.81    50.7 2146.93    60.7 2145.58    70.6 2146.52    80.7 2145.81
    83.9 2144.28    97.2 2133.79   103.9 2127.26   110.5  2123.7   113.8  2122.9
   123.8 2122.79   133.8    2121   155.2 2119.03   160.3 2118.71   163.6 2118.98
     167 2120.41   170.3 2125.99   176.9 2144.34   180.3 2151.79   196.9 2165.93
   200.2  2170.5   206.8 2183.48   210.2 2188.23   220.1 2198.49   272.3 2239.74
#Mann= 3 ,-1 , 0
       0      .1       0   155.2    .045       0   163.6      .1       0
Bank Sta=155.2,163.6
XS Rating Curve= 0 ,0
Exp/Cntr=0.3,0.1

Type RM Length L Ch R = 1 ,3012    ,201.4,201.4,201.4
XS GIS Cut Line= 2
2190354.74735598 377383.284025442190311.33974434 377650.85631805
#Sta/Elev= 30
       0 2173.59    17.8 2163.87    27.8 2155.26    31.3 2153.89    41.1 2152.48
    44.4 2150.56    51.1 2145.68      61 2137.11      71 2131.04    79.9 2126.35
    90.9 2123.05   104.2 2122.92   110.9 2121.87   117.5  2119.3   125.7 2113.91
   129.62112.875   144.1 2112.36   150.8 2112.96   154.1 2114.21   157.4 2116.97
   160.7 2121.79   167.4 2133.28   170.7 2137.93   197.2 2160.35   200.6  2164.2
   203.9 2168.83   217.2 2181.41   240.1 2199.85   248.6 2207.22   271.1 2224.53
#Mann= 3 ,-1 , 0
       0      .1       0   129.6    .045       0   150.8      .1       0
Bank Sta=129.6,150.8
XS Rating Curve= 0 ,0
Exp/Cntr=0.3,0.1

Type RM Length L Ch R = 1 ,2810    ,126.1,126.1,126.1
XS GIS Cut Line= 2
2190148.16034709377336.0276009282190155.44922768377635.939041553
#Sta/Elev= 30
       0 2145.39     5.8 2144.82    15.6 2140.96    28.8  2137.8    38.6 2136.05
    51.7 2131.47    54.9    2130    58.3 2127.89    64.9 2122.91    71.4 2117.47
    84.5  2108.1    87.8 2106.59    97.7 2103.81   104.2 2103.14   110.8 2102.52
   120.6 2103.14   130.5 2105.87   140.3 2109.54   143.6 2109.94   153.5 2109.77
   163.3 2110.94   166.6    2112   176.2 2116.04     193 2126.37   209.3 2137.08
   225.7 2148.31   251.9  2167.1   268.3  2179.4   279.2  2187.2     300 2201.43
#Mann= 3 ,-1 , 0
       0      .1       0   104.2    .045       0   120.6      .1       0
Bank Sta=104.2,120.6
XS Rating Curve= 0 ,0
Exp/Cntr=0.3,0.1