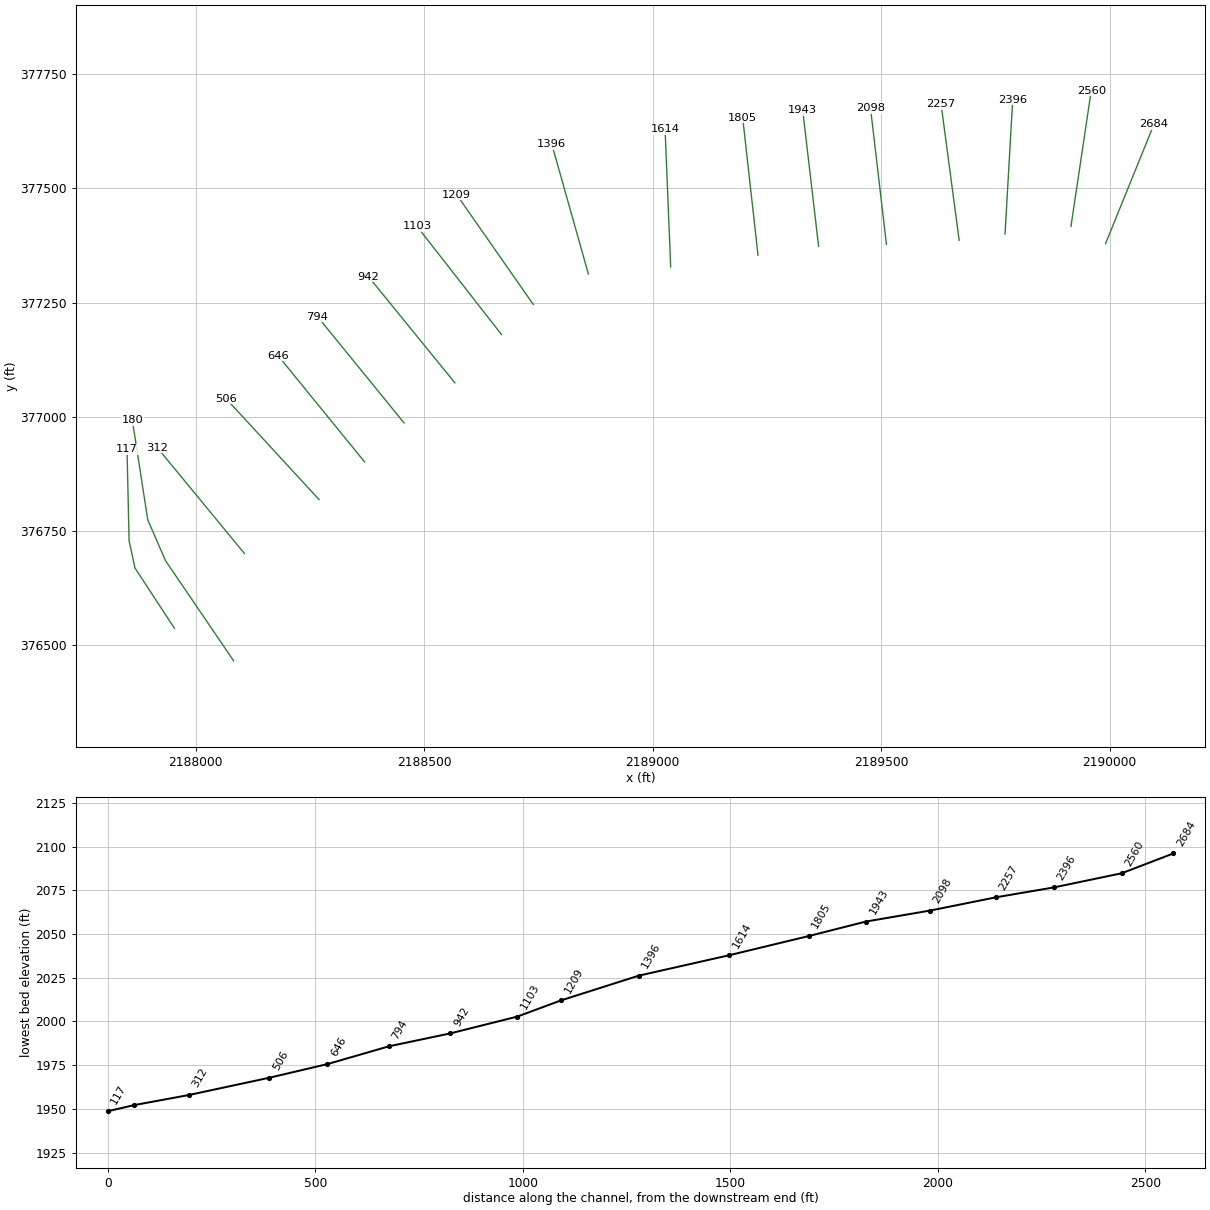
HEC-RAS study DAVYRN.prj: DAVYRN

--- DAVYRN.g01 (geometry) --- (continued)

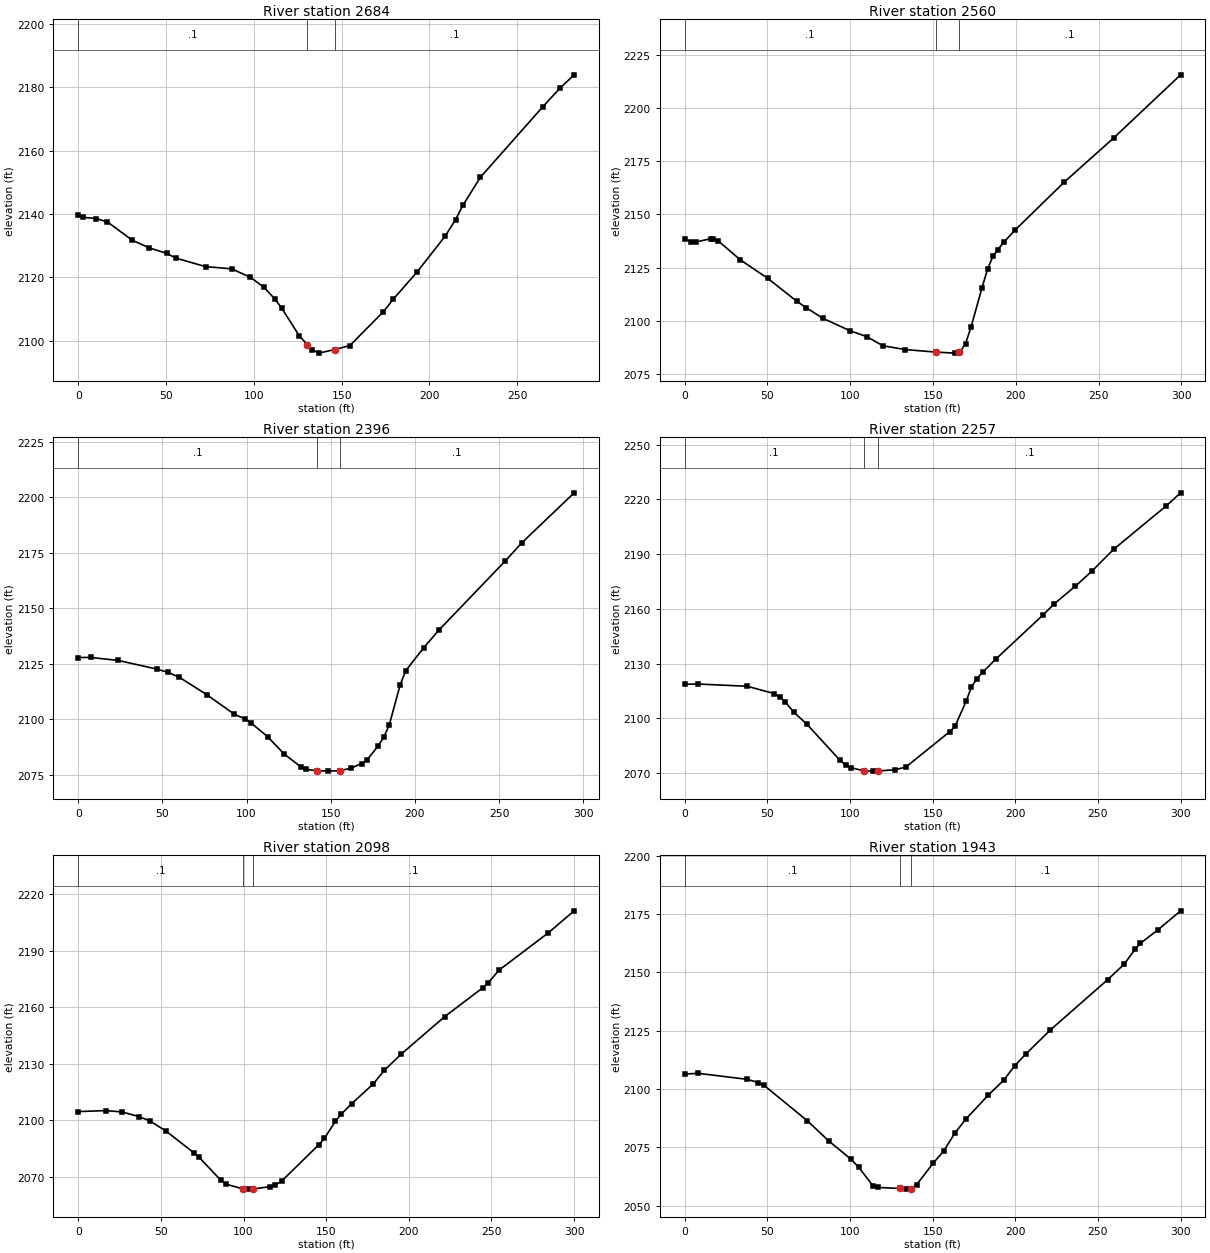
Type RM Length L Ch R = 1 ,2684    ,124.4,124.4,124.4
XS GIS Cut Line= 2
2189990.93464029377378.9164175052190097.07261597  377640.6014265
#Sta/Elev= 30
       0 2139.68     2.5 2138.95    10.1 2138.56    16.6  2137.5    30.8 2131.71
    40.3 2129.34    50.4 2127.56    55.6 2126.08    72.5  2123.4    87.4 2122.69
      98 2120.04   105.8 2116.88   112.2 2113.03   115.9 2110.27   125.9 2101.56
   130.52098.759   133.3 2097.26     137 2096.12     1462097.243   154.7 2098.51
   173.8 2109.19   179.5 2113.19   192.9 2121.66   209.1 2133.11   214.9 2138.24
   219.1 2142.78     229 2151.55   264.4  2173.7   274.5 2179.76   282.4 2183.86
#Mann= 3 , 0 , 0
       0      .1       0   130.5    .045       0     146      .1       0
Bank Sta=130.5,146
XS Rating Curve= 0 ,0
Exp/Cntr(USF)=0,0
Exp/Cntr=0.3,0.1

Type RM Length L Ch R = 1 ,2560    ,163.7,163.7,163.7
XS GIS Cut Line= 2
2189915.28180845 377416.865139692189959.54372768377713.052298906
#Sta/Elev= 30
       0 2138.55     3.7 2137.13       7 2137.08    15.8 2138.61      17 2138.63
    20.3 2137.55    33.6 2128.65    50.2 2119.92    67.8  2109.1    73.4 2106.12
    83.3 2101.22    99.9 2095.28   109.9 2092.56   119.7 2088.25   133.1 2086.45
   151.5 2085.27     163 2084.77   165.9 2085.28   166.3 2085.38   169.6 2089.19
   172.9 2096.94   179.5 2115.36   182.9 2124.29   186.2 2130.42     189 2133.35
   192.8 2137.02   199.4 2142.57   229.3 2165.27   259.2 2186.08   299.5 2215.69
#Mann= 3 ,-1 , 0
       0      .1       0   151.5    .045       0   165.9      .1       0
Bank Sta=151.5,165.9
XS Rating Curve= 0 ,0
Exp/Cntr=0.3,0.1

Type RM Length L Ch R = 1 ,2396    ,139.4,139.4,139.4
XS GIS Cut Line= 2
2189771.01216074377400.1287702712189787.85690555377694.263929686
#Sta/Elev= 30
       0 2127.82     7.3 2127.86    23.7 2126.51    46.7  2122.6    53.3 2121.13
    59.9 2119.01    76.3 2111.12    92.8 2102.24    99.3 2100.11   102.6 2098.39
   112.5 2092.17   122.3 2084.41   132.2  2078.6   135.5 2077.42   141.6 2076.89
   148.6 2076.66   155.32076.884   161.8  2077.9   168.3 2080.09   171.6 2081.75
   178.2 2088.04   181.5 2091.88   184.8 2097.54   191.3 2115.63   194.6 2121.93
   205.3 2132.29   214.3 2140.18   253.8  2171.4   263.6 2179.52   294.6 2201.97
#Mann= 3 ,-1 , 0
       0      .1       0   141.6    .045       0   155.3      .1       0
Bank Sta=141.6,155.3
XS Rating Curve= 0 ,0
Exp/Cntr=0.3,0.1

Type RM Length L Ch R = 1 ,2257    ,158.5,158.5,158.5
XS GIS Cut Line= 2
2189670.59932715377386.3802440292189631.15203437377683.775454303
#Sta/Elev= 30
       0 2118.62       8 2118.75    37.8 2117.53    54.3 2113.48    57.6 2111.68
    60.9 2108.78    66.2 2103.17    73.9 2096.76      94  2076.9    97.4 2074.31
   100.7 2072.85   108.2 2071.22   113.9 2071.01   117.2 2071.14   127.3 2071.76
   133.8 2073.25   160.2 2092.54   163.5 2095.48   170.2 2109.22   173.5 2117.16
   176.7 2121.71   180.7  2125.6   188.3 2132.51   216.5 2156.37   223.4 2162.59
   236.4 2172.43   246.3 2180.59   259.5  2192.6   291.4 2216.49     300 2223.55
#Mann= 3 ,-1 , 0
       0      .1       0   108.2    .045       0   117.2      .1       0
Bank Sta=108.2,117.2
XS Rating Curve= 0 ,0
Exp/Cntr=0.3,0.1

Type RM Length L Ch R = 1 ,2098    ,154.9,154.9,154.9
XS GIS Cut Line= 2
2189511.52827064377377.6272689942189476.66245827377675.594339528
#Sta/Elev= 30
       0 2104.61    16.7 2105.15    26.7 2104.39    36.6 2101.98    43.2 2099.73
    53.1 2094.27      70 2082.68      73 2080.45    86.2 2068.23    89.5 2066.04
    99.4  2063.6   102.7 2063.43     106 2063.55   115.9 2064.72   119.2 2065.58
   123.2 2067.83   145.6 2087.05   148.9 2090.32   155.5 2099.37     159 2103.14
   165.4 2108.78   178.6 2119.42   185.2 2126.56   195.2 2134.99   221.6 2154.99
   244.7 2170.35     248 2173.02   254.6 2179.75   284.4 2199.56     300 2211.23
#Mann= 3 ,-1 , 0
       0      .1       0    99.4    .045       0     106      .1       0
Bank Sta=99.4,106
XS Rating Curve= 0 ,0
Exp/Cntr=0.3,0.1

Type RM Length L Ch R = 1 ,1943    ,138.2,138.2,138.2
XS GIS Cut Line= 2
2189363.16494132377373.0921453832189328.29912896377671.059215931
#Sta/Elev= 30
       0 2106.42     8.1 2106.75    37.9 2104.16    44.5 2102.79    47.8 2101.72
    74.2  2086.4    87.4 2077.62   100.6 2069.96   105.2 2066.55   113.8 2058.65
   117.2 2057.85   130.4  2057.4   133.7 2057.13     137 2057.39   140.3 2059.04
   150.2 2068.14   156.8 2073.55   163.4 2081.09     170 2087.06   183.7 2097.44
   193.1 2103.88   199.7 2110.04   206.3 2114.97   221.2 2125.31   255.9 2146.88
   265.8 2153.47   272.4 2159.84   275.7 2162.45   286.3 2168.24     300 2176.36
#Mann= 3 ,-1 , 0
       0      .1       0   130.4    .045       0     137      .1       0
Bank Sta=130.4,137
XS Rating Curve= 0 ,0
Exp/Cntr=0.3,0.1

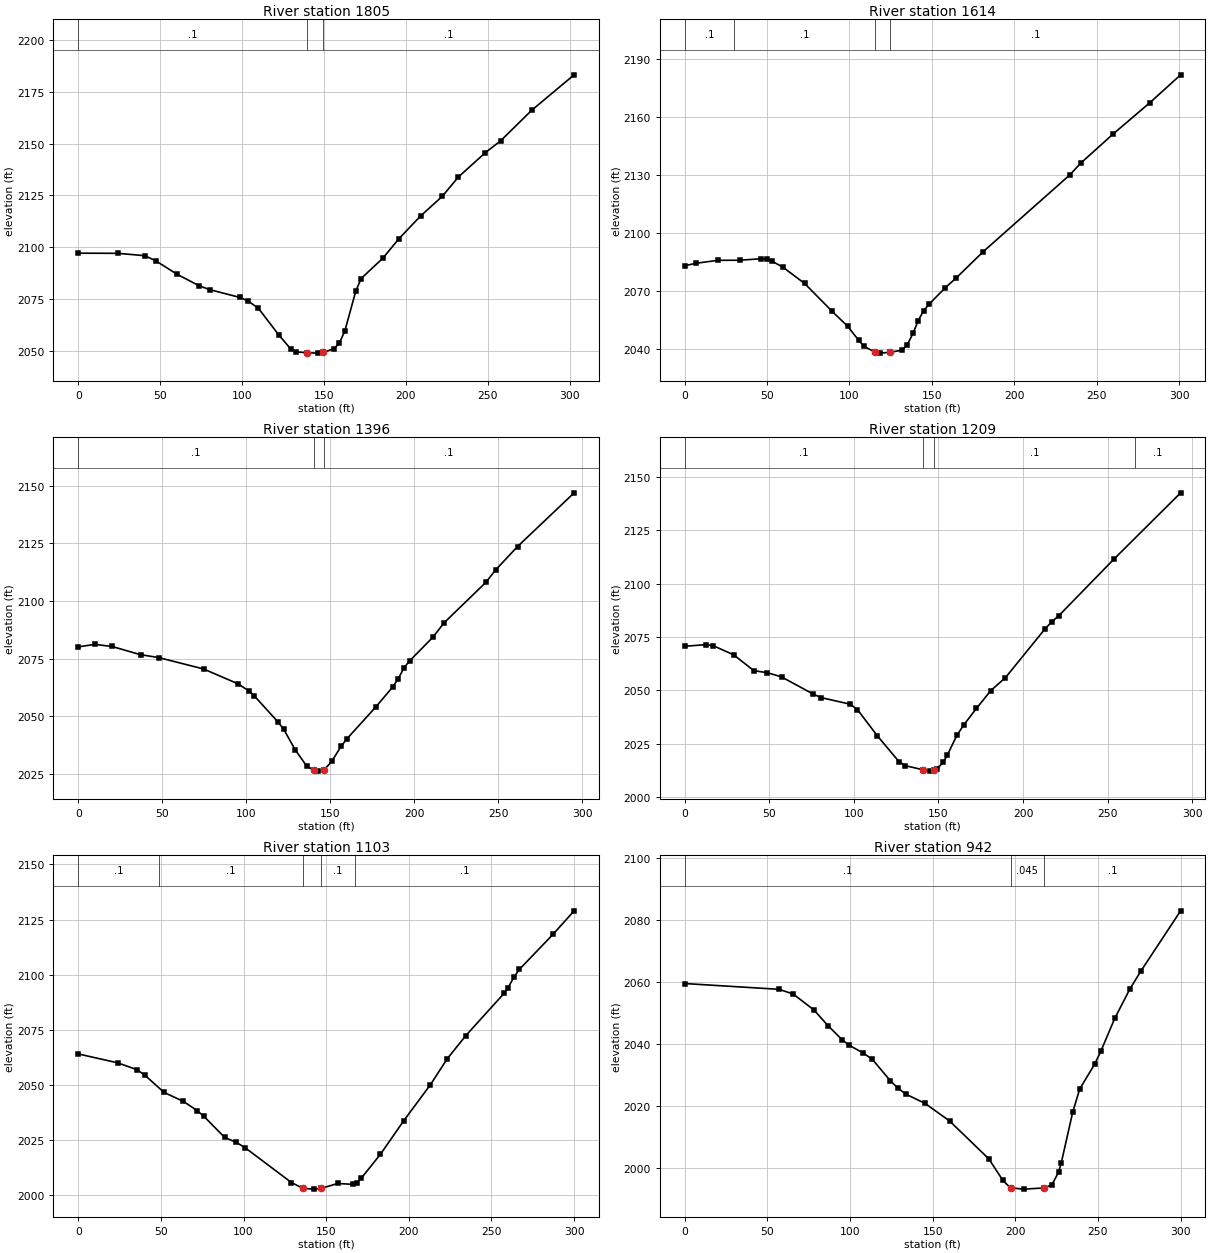
Type RM Length L Ch R = 1 ,1805    ,190.4,190.4,190.4
XS GIS Cut Line= 2
2189230.59674363377353.9935538372189196.99508751 377654.74356686
#Sta/Elev= 30
       0 2097.08    24.1 2097.01    40.6 2095.87    47.2 2093.45    60.4 2086.85
    73.6 2081.42    80.2 2079.47    98.7 2075.69   103.3 2074.14   109.9 2070.51
   122.4 2057.56   129.7 2050.81     133 2049.42   139.3 2049.02   146.2 2048.81
   149.5 2049.12   156.1 2050.99   159.4 2053.73   162.7 2059.55   169.3  2078.6
   172.6 2084.84   185.8 2094.59   195.7 2104.08   208.9 2115.04   222.1  2124.5
     232 2133.91   248.5 2145.68   257.7 2151.32   276.8 2166.17   302.6 2183.21
#Mann= 3 ,-1 , 0
       0      .1       0   139.3    .045       0   149.5      .1       0
Bank Sta=139.3,149.5
XS Rating Curve= 0 ,0
Exp/Cntr=0.3,0.1

Type RM Length L Ch R = 1 ,1614    ,218.5,218.5,218.5
XS GIS Cut Line= 2
 2189039.5365289 377328.166941132189027.25188978377628.828574844
#Sta/Elev= 30
       0 2083.05     7.1 2084.36    20.2 2085.85    33.4 2085.89    46.5 2086.68
    49.8 2086.34    53.1 2085.35    59.6  2082.3    72.8 2073.88    89.2 2059.71
      99 2051.69   105.6 2044.47   108.9 2041.36   115.4 2038.45   118.7 2037.91
   124.8 2038.37   131.9 2039.43   135.1 2042.24   138.5 2048.06   141.7 2054.72
     145 2059.88   148.3 2063.19   158.1 2071.69   164.7  2076.7   181.1 2090.31
   233.7 2129.99   240.2 2135.98   259.9 2151.07   282.3 2167.32   300.9 2181.67
#Mann= 4 ,-1 , 0
       0      .1       0   30.13      .1       0   115.4    .045       0
   124.8      .1       0
Bank Sta=115.4,124.8
XS Rating Curve= 0 ,0
Exp/Cntr=0.3,0.1

Type RM Length L Ch R = 1 ,1396    ,187.1,187.1,187.1
XS GIS Cut Line= 2
2188859.45231645377312.6656722052188779.35137458377596.685261045
#Sta/Elev= 30
       0 2080.07     9.8 2081.16    20.1 2080.25    37.1 2076.69    47.8 2075.45
    74.6 2070.49    95.1 2064.05   101.9 2060.79   104.8  2058.8   118.9  2047.5
   122.3 2044.29   129.1 2035.47     136 2028.32   140.1  2026.7   142.8 2026.19
   146.2 2026.63   150.8 2030.37   156.4 2036.91   159.8 2040.15   176.9 2053.86
   187.1 2062.66   190.5 2066.32   193.9 2071.09   197.3 2074.08     211 2084.23
   217.8 2090.59   242.5 2108.01   248.4 2113.46   261.4 2123.59   295.1 2146.89
#Mann= 3 ,-1 , 0
       0      .1       0   140.1    .045       0   146.2      .1       0
Bank Sta=140.1,146.2
XS Rating Curve= 0 ,0
Exp/Cntr=0.3,0.1

Type RM Length L Ch R = 1 ,1209    ,105.5,105.5,105.5
XS GIS Cut Line= 2
2188738.94760356377245.9345677482188571.14803024377486.296118759
#Sta/Elev= 30
       0 2070.59    12.5 2071.34    16.9 2070.84    28.9  2066.6    40.9 2059.15
    48.9 2058.19    57.3  2056.2    76.1 2048.11    80.8 2046.49    97.9 2043.42
   102.1 2040.91   113.8 2028.66   126.6 2016.57   130.3 2014.63   140.9 2012.69
   144.9 2012.06   147.6 2012.61   149.2 2013.12   152.9 2016.36   155.3 2019.72
   160.9 2028.86   164.9 2033.67   172.4 2041.43   180.9 2049.79   189.6 2055.91
   212.8 2078.57     217 2082.11     221 2084.83   253.6 2111.36   293.1 2142.51
#Mann= 4 ,-1 , 0
       0      .1       0   140.9    .045       0   147.6      .1       0
  266.42      .1       0
Bank Sta=140.9,147.6
XS Rating Curve= 0 ,0
Exp/Cntr=0.3,0.1

Type RM Length L Ch R = 1 ,1103    ,161.1,161.1,161.1
XS GIS Cut Line= 2
2188669.44956632377180.1137512622188484.75075838377416.516691914
#Sta/Elev= 30
       0 2064.08    23.8 2060.06    35.5 2056.96    40.2 2054.51    51.9 2046.64
    63.6 2042.57      72 2038.36    76.1 2035.73    88.6 2026.21    95.4 2024.08
     101 2021.54     129 2005.76     136  2003.1   142.7 2002.78   146.9 2003.11
     157 2005.34   166.4 2004.94   168.7 2005.76   171.1  2007.6   182.8 2018.57
   196.9 2033.78   213.1 2050.17   223.3 2061.96   234.3 2072.23   257.6 2091.54
   259.9 2093.94   263.5 2098.83   266.9 2102.44   287.3 2118.37     300 2128.96
#Mann= 5 ,-1 , 0
       0      .1       0   48.98      .1       0     136    .045       0
   146.9      .1       0  167.57      .1       0
Bank Sta=136,146.9
XS Rating Curve= 0 ,0
Exp/Cntr=0.3,0.1

Type RM Length L Ch R = 1 ,942     ,148.1,148.1,148.1
XS GIS Cut Line= 2
2188567.52507936377074.4480991222188378.08177441 377307.06631468
#Sta/Elev= 30
       0  2059.6    57.1 2057.73    65.6 2056.22    78.2 2051.06    86.7 2045.98
    95.2 2041.46    99.4 2039.69   107.9 2037.19   113.5 2035.11   124.4  2028.2
     129 2025.81   133.7  2023.9   145.4 2020.87   160.2 2015.22     184 2002.95
   192.5 1995.99   197.11993.586   205.2 1993.18   217.4 1993.56   222.1 1994.58
   226.3 1998.76   227.8 2001.66   234.8 2018.21     239 2025.57     248 2033.55
   251.7 2037.68   260.2 2048.39   269.3 2057.82   275.9 2063.57     300 2083.09
#Mann= 3 ,-1 , 0
       0      .1       0   197.1    .045       0   217.4      .1       0
Bank Sta=197.1,217.4
XS Rating Curve= 0 ,0
Exp/Cntr=0.3,0.1

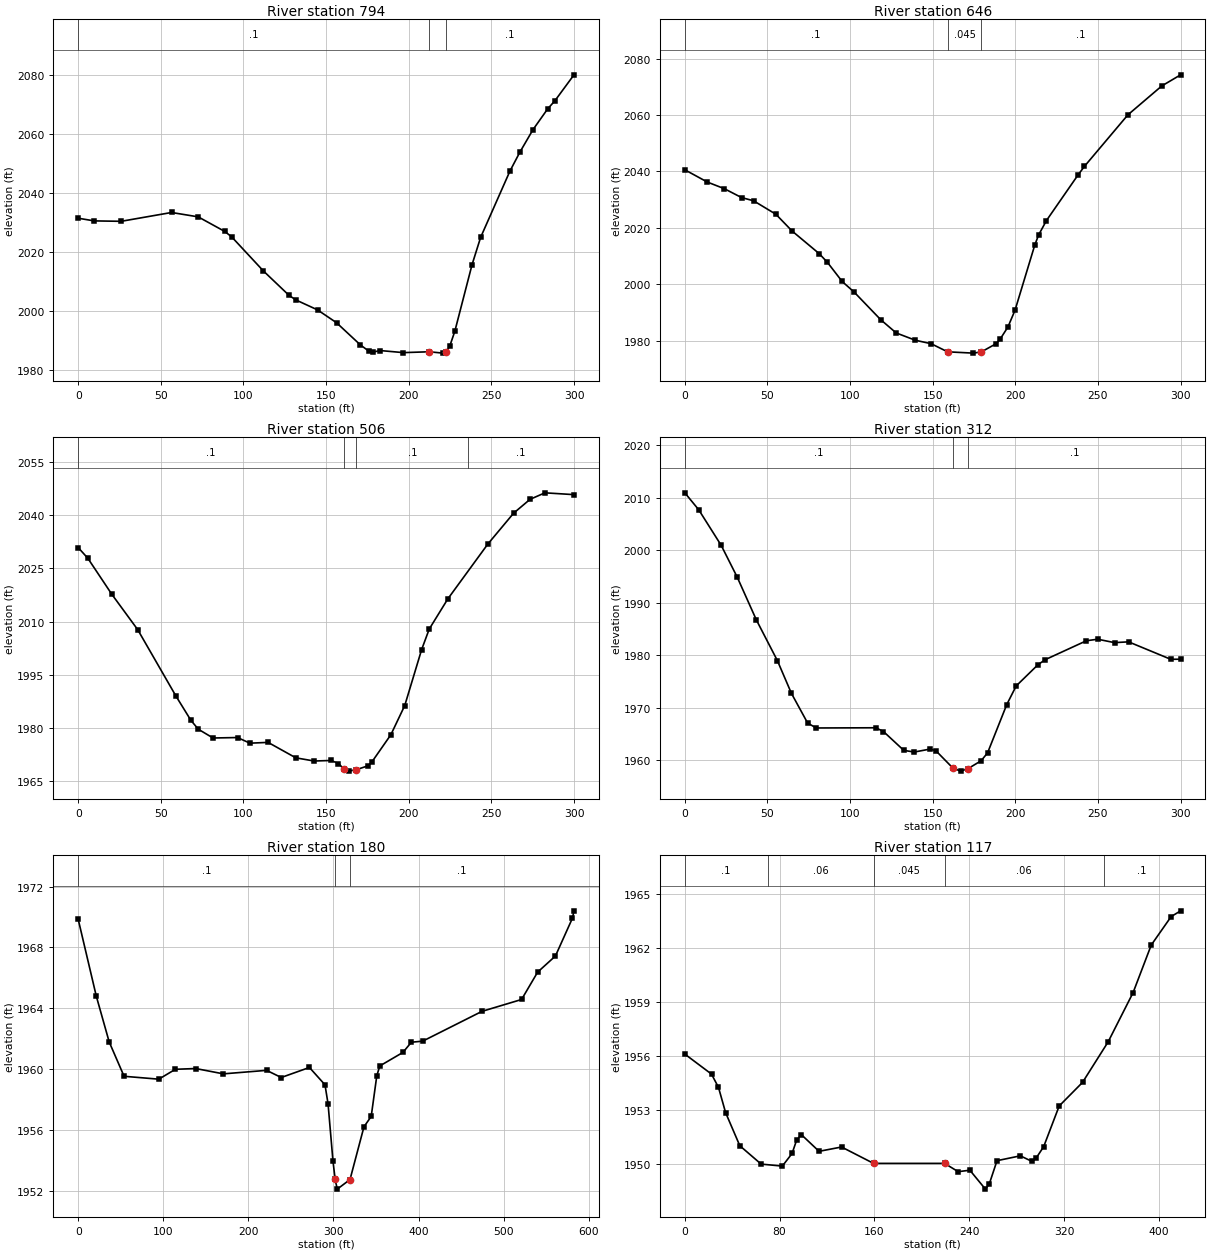
Type RM Length L Ch R = 1 ,794     ,148.3,148.3,148.3
XS GIS Cut Line= 2
2188456.09061368376986.9850010562188266.64730872377219.603216613
#Sta/Elev= 30
       0  2031.5     9.7 2030.59      26 2030.45    56.5 2033.44    72.6 2031.96
    88.7 2027.01    92.9 2025.16     112 2013.66   127.6 2005.34   131.8 2003.78
   144.8 2000.44   156.3 1996.09   170.8 1988.54     176  1986.4   178.4 1986.11
   182.6 1986.66   196.8 1985.95   212.4 1986.24   220.7 1985.78   222.7 1986.12
   224.9 1988.27   227.9  1993.2   238.3 2015.73   243.5 2024.99   261.2 2047.42
   267.2 2053.83   275.2 2061.52   284.1 2068.57   288.4 2071.26     300 2080.09
#Mann= 3 ,-1 , 0
       0      .1       0   212.4    .045       0   222.7      .1       0
Bank Sta=212.4,222.7
XS Rating Curve= 0 ,0
Exp/Cntr=0.3,0.1

Type RM Length L Ch R = 1 ,646     ,140,140,140
XS GIS Cut Line= 2
2188369.92326521376901.4655273972188180.47996026377134.083742945
#Sta/Elev= 30
       0  2040.6    13.6 2036.25    23.9  2033.9    34.3 2030.76    41.6 2029.61
    55.1 2024.83    64.9 2018.89    81.3 2010.87    86.3 2007.76    95.2    2001
   102.5 1997.21   118.5 1987.46   127.9 1982.75   139.5 1980.16     149 1978.95
     159 1976.06   174.6  1975.6   179.4 1976.03   188.5 1978.99   190.8 1980.57
   195.5 1984.87   199.8 1990.82   211.8 2014.02   214.1 2017.54   218.8  2022.6
   237.9 2038.75   241.8 2041.82   268.1 2060.09   288.6 2070.33     300 2074.27
#Mann= 3 ,-1 , 0
       0      .1       0     159    .045       0   179.4      .1       0
Bank Sta=159,179.4
XS Rating Curve= 0 ,0
Exp/Cntr=0.3,0.1

Type RM Length L Ch R = 1 ,506     ,194,194,194
XS GIS Cut Line= 2
2188270.16357136 376819.188141842188066.89176977377039.824890091
#Sta/Elev= 30
       0 2030.88     5.8 2027.89    20.3 2017.73      36 2007.72    59.1 1989.01
    68.2 1982.12    72.7 1979.61    81.6 1977.14    96.4 1977.27   103.9 1975.68
   114.9  1975.9   131.7 1971.54   142.8 1970.64     153  1970.8   157.5 1969.94
   160.8 1968.36   163.7 1967.79   168.3  1968.2   175.3 1969.28   177.6 1970.31
   189.2 1978.07   197.6 1986.31   207.8 2002.08   212.4 2007.88   223.7 2016.43
   247.9  2031.9   263.5 2040.61   273.4  2044.5   282.4 2046.34     300 2045.83
#Mann= 4 ,-1 , 0
       0      .1       0   160.8    .045       0   168.3      .1       0
  236.14      .1       0
Bank Sta=160.8,168.3
XS Rating Curve= 0 ,0
Exp/Cntr=0.3,0.1

Type RM Length L Ch R = 1 ,312     ,132.2,132.2,132.2
XS GIS Cut Line= 2
2188106.78812116376701.4379914672187916.08391502376933.023625227
#Sta/Elev= 30
       0 2010.92     8.4 2007.69      22 2000.91    31.7 1994.85    43.3 1986.69
      56 1978.95    64.5 1972.71    74.3 1967.06    79.5 1966.12   115.6 1966.16
   120.2 1965.44   132.5 1961.85   138.9 1961.54   148.2 1962.09   151.8 1961.82
   162.2 1958.48   166.9  1957.9   171.5  1958.4   179.3 1959.88   183.2 1961.39
   194.8 1970.59   200.5 1974.13   213.7 1978.18   218.1 1979.14     243 1982.74
   249.8 1983.03     260 1982.38   268.5 1982.53     294 1979.21     300 1979.22
#Mann= 3 ,-1 , 0
       0      .1       0   162.2    .045       0   171.5      .1       0
Bank Sta=162.2,171.5
XS Rating Curve= 0 ,0
Exp/Cntr=0.3,0.1

Type RM Length L Ch R = 1 ,180     ,63.3,63.3,63.3
XS GIS Cut Line= 4
2188083.29830547376466.5411827652187934.28710135376685.522865339
2187895.41461332376774.929587798 2187861.7251237376992.615520756
#Sta/Elev= 30
       0 1969.85    21.3 1964.79    36.4 1961.79    53.9 1959.53    94.7 1959.34
   114.2 1959.99     138 1960.04   170.6 1959.69   221.4 1959.92   238.6 1959.45
   271.7 1960.11     290 1958.97   293.6 1957.72   299.4 1953.95   301.9 1952.77
   304.4 1952.11   319.4 1952.74   335.8 1956.21   344.3 1956.89   350.9 1959.57
   354.4 1960.21   381.6  1961.1   391.5 1961.77   404.8 1961.84   474.5  1963.8
     521 1964.58   539.9 1966.38   560.8 1967.44   580.8 1969.93   582.6 1970.41
#Mann= 3 ,-1 , 0
       0      .1       0   301.9    .045       0   319.4      .1       0
Bank Sta=301.9,319.4
XS Rating Curve= 0 ,0
Exp/Cntr=0.3,0.1

Type RM Length L Ch R = 1 ,117     ,117,117,117
XS GIS Cut Line= 4
2187953.72334537376537.807410814 2187867.5559969376669.325995312
2187854.59850089 376728.930476962187850.06337729376929.123790322
#Sta/Elev= 30
       0 1956.13    22.5 1955.02    28.4 1954.28    34.4 1952.88    46.4 1951.04
    64.4 1950.02    82.3 1949.91    90.5 1950.61    94.3 1951.34    98.3 1951.66
   113.3 1950.73   132.3 1950.97   159.3 1950.06   219.3 1950.06   230.7  1949.6
   240.6 1949.68   253.7 1948.63     257 1948.92   263.5 1950.21   283.2 1950.48
     293 1950.17   296.4 1950.34   302.9 1950.99     316 1953.25   335.7 1954.56
   357.3 1956.81   378.4 1959.55   393.7 1962.19   410.5 1963.77   418.5 1964.09
#Mann= 5 ,-1 , 0
       0      .1       0   69.89     .06       0   159.3    .045       0
   219.3     .06       0  353.57      .1       0
#XS Ineff= 2 , 0
           98.78 1951.63
Permanent Ineff=
       F       F
Bank Sta=159.3,219.3
XS Rating Curve= 0 ,0
Exp/Cntr=0.3,0.1
LCMann Table=0

Chan Stop Cuts=-1
Use User Specified Reach Order=0
Composite Channel Slope=5